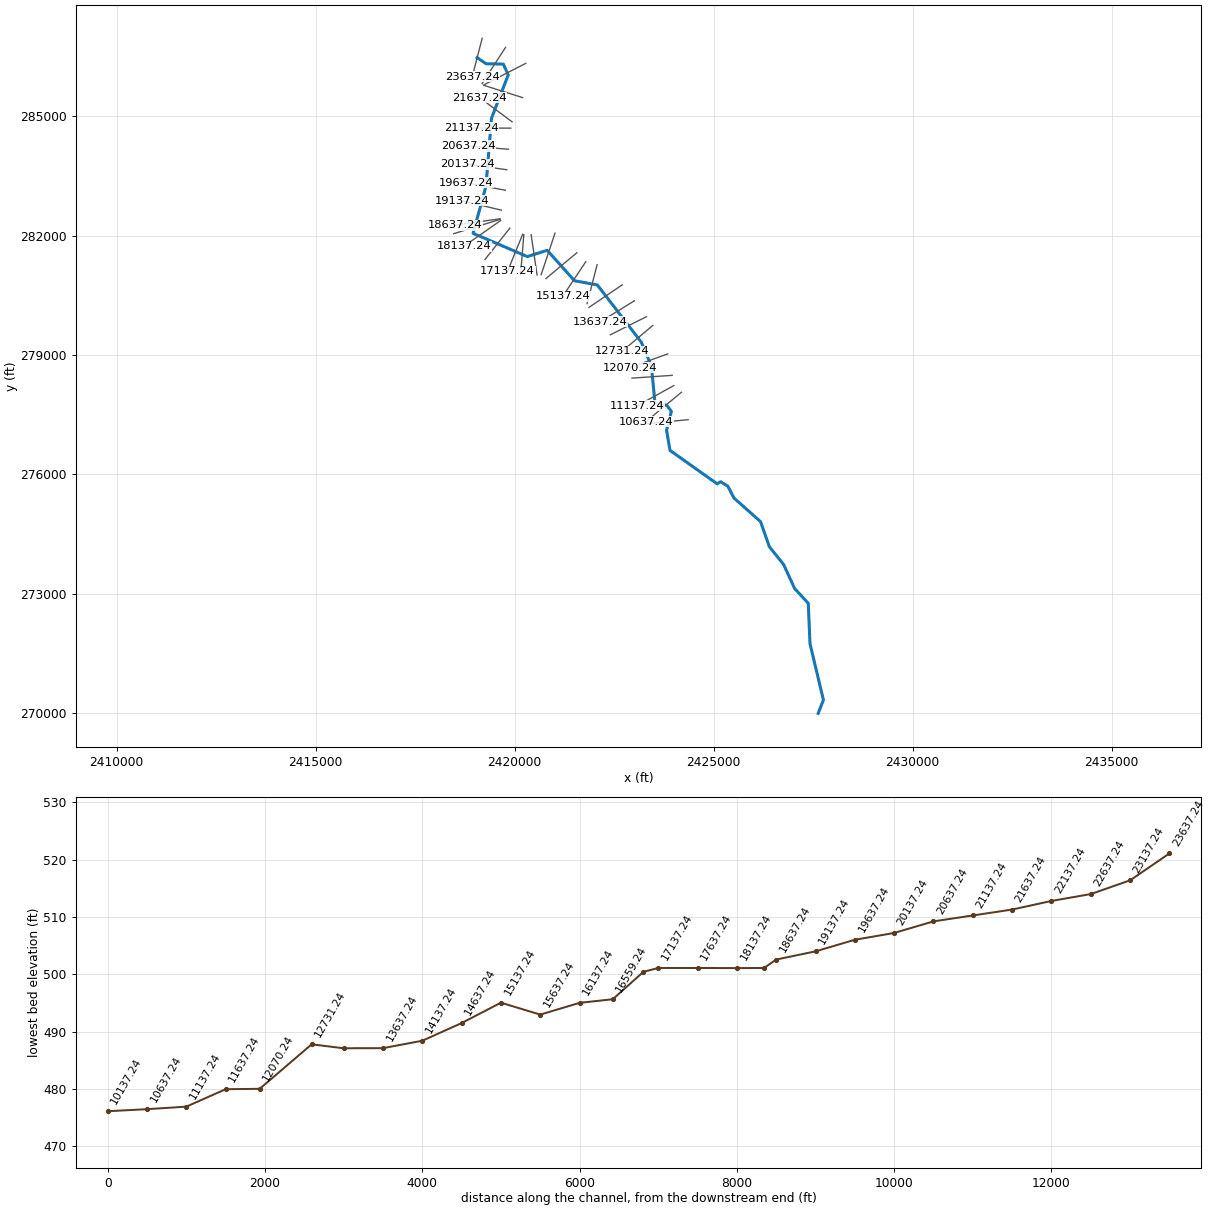
--- NorthForkBullskinRu.prj (project) ---

Proj Title=NorthForkBullskinRun
Current Plan=p01
Default Exp/Contr=0.3,0.1
English Units
Geom File=g01
Flow File=f01
Plan File=p01
Y Axis Title=Elevation
X Axis Title(PF)=Main Channel Distance
X Axis Title(XS)=Station
BEGIN DESCRIPTION:
END DESCRIPTION:
DSS Export Rating Curves= 0
DSS Export Rating Curve Sorted= 0
DSS Export Volume Flow Curves= 0
DXF OffsetX= 0
DXF OffsetY= 0
DXF ScaleX= 1
DXF ScaleY= 10

--- NorthForkBullskinRu.p01 (plan) ---

Plan Title=Plan 01
Program Version=4.10
Short Identifier=Plan 01
Geom File=g01
Flow File=f01
Subcritical Flow
K Sum by GR= 0
Std Step Tol= 0.01
Critical Tol= 0.01
Num of Std Step Trials= 20
Max Error Tol= 0.3
Flow Tol Ratio= 0.001
Split Flow NTrial= 30
Split Flow Tol= 0.02
Split Flow Ratio= 0.02
Log Output Level= 0
Friction Slope Method= 1
Unsteady Friction Slope Method= 2
Unsteady Bridges Friction Slope Method= 1
Parabolic Critical Depth
Global Vel Dist= 0 , 0 , 0
Global Log Level= 0
CheckData=True
Encroach Param=-1 ,0,0, 0
Computation Interval=1HOUR
Output Interval=1HOUR
Run HTab= 0
Run UNet= 0
Run PostProcess= 0
Run WQNet= 0
UNET Theta= 1
UNET Theta Warmup= 1
UNET ZTol= 0.02
UNET ZSATol= 0.05
UNET MxIter= 20
UNET MaxInSteps= 0
UNET DtIC= 0
UNET DtMin= 0
UNET MaxCRTS= 20
UNET WFStab= 2
UNET SFStab= 1
UNET WFX= 1
UNET SFX= 1
UNET DSS MLevel= 4
UNET DZMax Abort= 100
UNET Convert EG Bridges= 0
UNET Use Existing IB Tables=-1
UNET Froude Reduction=False
UNET Froude Limit= 1
UNET Froude Power= 10
UNET Time Slicing=0,0, 5
UNET Junction Losses=0
Instantaneous Interval=1HOUR
Write IC File= 0
Write IC File at Sim End=0
Echo Input=False
Echo Parameters=False
Echo Output=False
Write Detailed= 0
WQ AD Non Conservative
WQ ULTIMATE=-1
WQ Max Comp Step=1HOUR
WQ Output Interval=15MIN
WQ Output Selected Increments= 0
WQ Output face flow=0
WQ Output face velocity=0
WQ Output face area=0
WQ Output face dispersion=0
WQ Output cell volume=0
WQ Output cell surface area=0
WQ Output cell continuity=0
WQ Output cumulative cell continuity=0
WQ Output face conc=0
WQ Output face dconc_dx=0
WQ Output face courant=0
WQ Output face peclet=0
WQ Output face adv mass=0
WQ Output face disp mass=0
WQ Output cell mass=0
WQ Output cell source sink temp=0
WQ Output cell source sink nsm=0
WQ Output MaxMinRange=-1
WQ Daily Max Min Mean=-1
WQ Daily Range=0
WQ Daily Time=0
WQ Create Restart=0
WQ Fixed Restart=0
WQ System Summary=0
WQ Use Fixed Temperature=0
Sorting and Armoring Iterations= 10
XS Update Threshold= 0.02
Hydraulics Update Threshold= 0.02
Energy Slope Method= 1
Volume Change Method= 0
XS Weighting Method= 0
Number of US Weighted Cross Sections= 1
Number of DS Weighted Cross Sections= 1
Upstream XS Weight=0.25
Main XS Weight=0.5
Downstream XS Weight=0.25
Number of DS XS's Weighted with US Boundary= 1
Upstream Boundary Weight= 1
Weight of XSs Associated with US Boundary= 0
Number of US XS's Weighted with DS Boundary= 1
Downstream Boundary Weight= 0.5
Weight of XSs Associated with DS Boundary= 0.5
Sediment Output Level= 4
Mass or Volume Output= 0
Output Increment Type= 1
Profile and TS Output Increment= 10
XS Output Flag= 0
XS Output Increment= 10
Disregard all LS=0
Disregard all Conn=0
Disregard all Breaches=0
Disregard all Pumps=0

--- NorthForkBullskinRu.f01 (steady flow) ---

Flow Title=Flow1
Program Version=4.10
Number of Profiles= 1
Profile Names=PF 1
River Rch & RM=NrthFrkBullSknRn,Reach1          ,23637.24
     298
River Rch & RM=NrthFrkBullSknRn,Reach1          ,22637.24
    1285
River Rch & RM=NrthFrkBullSknRn,Reach1          ,5637.244
    1563
Boundary for River Rch & Prof#=NrthFrkBullSknRn,Reach1          , 1
Up Type= 0
Dn Type= 3
Dn Slope=0.0033
DSS Import GetInterval= 0
DSS Import GetPeak= 0
DSS Import FillOption= 0

--- NorthForkBullskinRu.g01 (geometry) ---

Geom Title=Geo1
Program Version=4.10

River Reach=NrthFrkBullSknRn,Reach1
Reach XY= 30
2419059.11455694286473.8564380262419280.96286653286319.958779931
2419718.78646594286310.394822687 2419840.7242142286038.164067939
2419420.04690593284950.2466243512419281.08819436283241.133244693
2418958.01469353282058.6162527652420320.35940978281474.644323602
2420820.71602061281631.9576572632421506.19594885280867.162927017
2422080.86376278280761.2130076892423182.19128452 279326.91436711
2423436.52509344278730.7308481932423529.49341144277781.079532266
2423825.64701861277739.976268023 2423939.1723821277586.019883022
2423819.08928894277109.8955071872423904.86700453276605.127815932
2425091.89579844275763.0235290232425176.84838444275817.459115684
2425361.26993161275701.9895303552425510.55605036275410.016032934
2426179.78535494274815.3469466872426401.48733936274186.036853597
2426760.92822152273735.7047490182427036.81841777273133.612777352
2427379.10349436 272763.284777852427423.47709328271744.676906943
2427759.98888744270334.2965255982427628.02327211269996.959929943

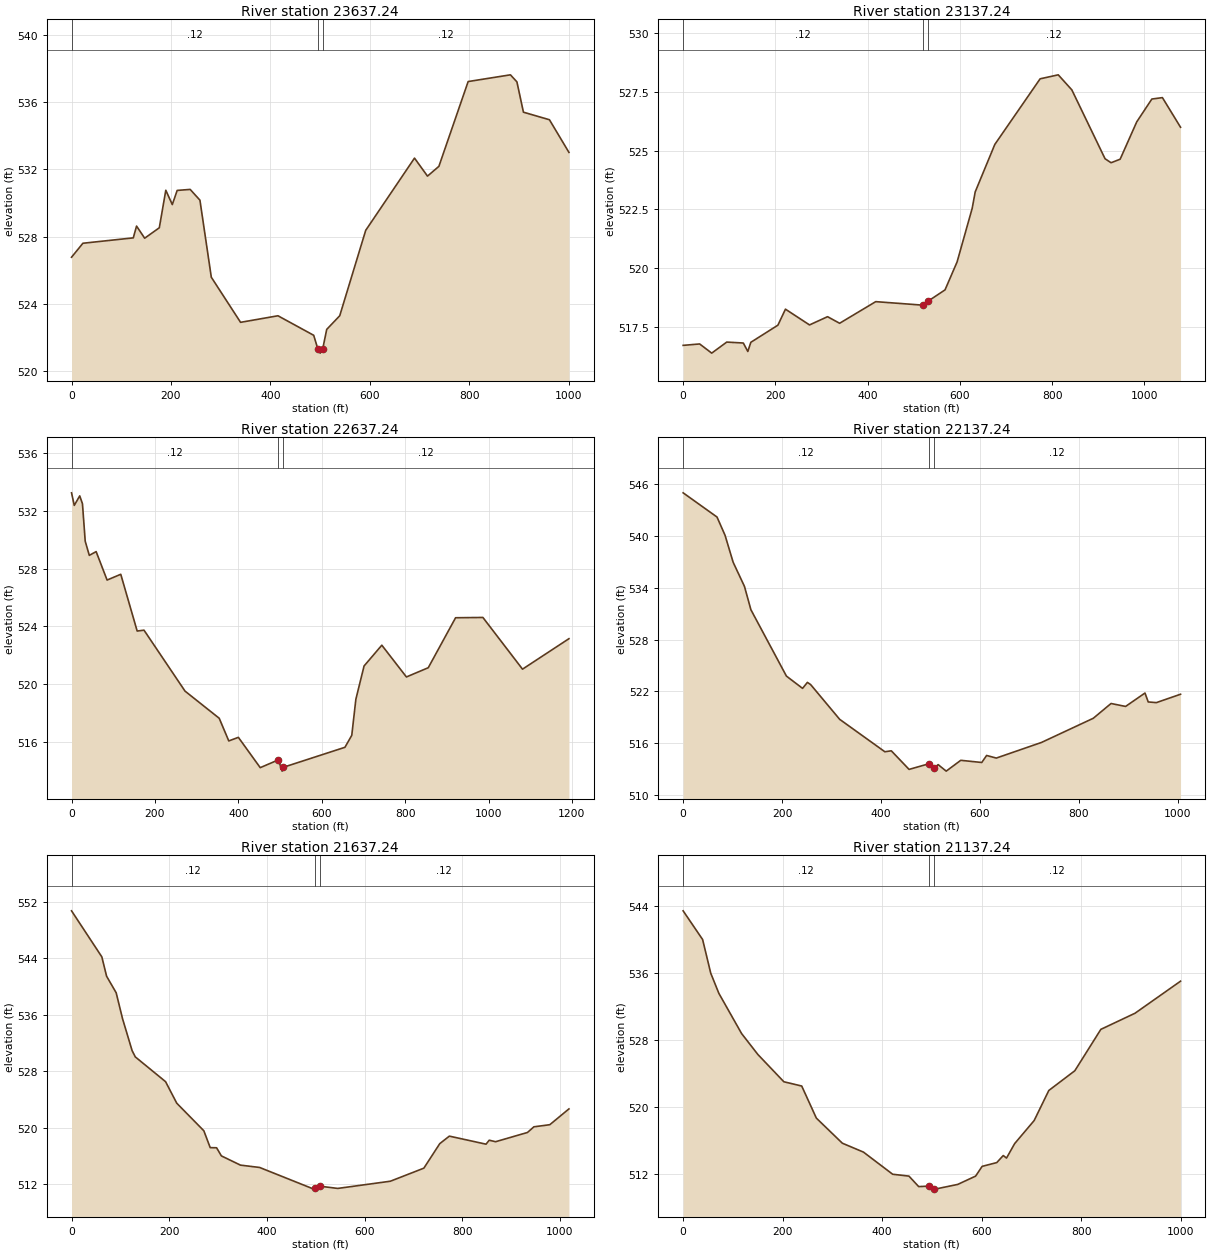
Type RM Length L Ch R = 1 ,23637.24,507.69,500,488.43
Node Name=1040
XS GIS Cut Line= 3
2419185.90662619286957.8846694382419061.07026169286473.438131765
2418936.20141694285988.865938187
#Sta/Elev= 30
       0  526.77   22.89   527.6  124.25  527.92  130.79  528.62  147.14   527.9
  176.57  528.52  189.65  530.75  202.72   529.9  212.53  530.74  238.69   530.8
  258.31  530.16   281.2  525.58  340.05   522.9  415.26  523.29  487.19  522.13
   495.5  521.32  500.27  521.07   505.3  521.32  513.36  522.48  539.52  523.29
  591.85  528.37  689.97  532.66  716.13  531.59  739.03  532.17   797.9  537.21
  882.93  537.61  896.02  537.19   909.1  535.39  961.43  534.94 1000.68     533
#Mann= 3 , 0 , 0
       0     .12       0   495.5    .045       0   505.3     .12       0
Bank Sta=495.5,505.3
XS Rating Curve= 0 ,0
Exp/Cntr=0.3,0.1

Type RM Length L Ch R = 1 ,23137.24,512.15,500,483.49
Node Name=1041
XS GIS Cut Line= 3
2419771.66660953286728.4428711092419486.19900461286287.491653264
2419185.53129886285823.061151683
#Sta/Elev= 30
       0  516.71   35.89  516.77   61.99  516.38   94.62  516.85  130.51  516.81
  140.29  516.45  146.82  516.84  205.55  517.57  221.86  518.25  274.06  517.58
  313.22  517.93  339.32  517.65  417.62  518.57  520.29  518.42  530.24  518.58
  567.85  519.07  594.04  520.26  626.78  522.54  633.32  523.24  675.88  525.26
  774.09  528.05  813.38  528.22  842.84  527.58  914.86  524.65  927.96  524.48
   947.6  524.63  983.61  526.22 1016.35  527.19 1039.26  527.25 1078.55  525.99
#Mann= 3 , 0 , 0
       0     .12       0  520.29    .045       0  530.24     .12       0
Bank Sta=520.29,530.24
XS Rating Curve= 0 ,0
Exp/Cntr=0.3,0.1

Type RM Length L Ch R = 1 ,22637.24,523.17,500,474.13
Node Name=1042
XS GIS Cut Line= 3
2420281.56060286286329.0742472712419835.13695502 286100.13047944
2419220.16771252285784.749876603
#Sta/Elev= 30
       0  533.25    6.56  532.38   19.67  533.04   26.23  532.49   32.79   529.9
   42.63  528.92   59.02  529.18   85.26  527.21  118.05  527.61   157.4  523.68
  173.79  523.74  272.17  519.52  354.15  517.64   377.1  516.07  400.05  516.32
  452.52  514.22  496.12  514.76  504.98  513.98   507.3  514.24  655.65  515.63
  672.03  516.46  681.86  518.96  701.51  521.26  744.09   522.7  803.05   520.5
  855.46  521.14  920.97   524.6  986.48  524.62 1081.47  521.04 1192.83  523.15
#Mann= 3 , 0 , 0
       0     .12       0  496.12    .045       0   507.3     .12       0
Bank Sta=496.12,507.3
XS Rating Curve= 0 ,0
Exp/Cntr=0.3,0.1

Type RM Length L Ch R = 1 ,22137.24,509.68,500,489.56
Node Name=1043
XS GIS Cut Line= 3
 2420201.8455392285468.9217680992419722.70017202285620.622580186
2419242.90782453285772.528116271
#Sta/Elev= 30
       0  544.96   68.53  542.16   84.85  540.04  101.17  536.93  124.02  534.14
  137.07  531.44  208.87  523.77   241.5  522.35  251.29  523.04  257.82  522.79
  316.56  518.77  407.94  515.02     421  515.13   456.9  512.98  497.57  513.64
  507.59  513.16  515.66  513.53     532  512.78  561.41  514.03  603.89  513.78
   613.7  514.59   633.3  514.29  724.81   516.1  829.38  518.89  865.33   520.6
  894.74  520.26  933.96  521.81  940.49  520.78  956.83   520.7 1005.85  521.67
#Mann= 3 , 0 , 0
       0     .12       0  497.57    .045       0  507.59     .12       0
Bank Sta=497.57,507.59
XS Rating Curve= 0 ,0
Exp/Cntr=0.3,0.1

Type RM Length L Ch R = 1 ,21637.24,480.04,500,518.51
Node Name=1044
XS GIS Cut Line= 3
2419937.18530735284860.695950434 2419534.1165597285160.929601938
2419120.43759702 285469.06678094
#Sta/Elev= 30
       0  550.72   62.01   544.2    71.8  541.45   91.38  539.11  104.44  535.43
  124.02  530.91  130.54  530.02  192.55  526.51   215.4  523.46  270.88  519.55
  283.94  517.16  296.99  517.14  306.78  515.99  345.94  514.68  385.11  514.35
  496.07  511.28  498.08  511.47  508.09   511.7  545.04  511.38  652.78   512.4
  721.34  514.25  753.98  517.73  773.57  518.79  848.66  517.65  855.19  518.21
  868.25     518  933.54  519.31   946.6  520.11  979.25  520.41 1018.43  522.65
#Mann= 3 , 0 , 0
       0     .12       0  498.08    .045       0  508.09     .12       0
Bank Sta=498.08,508.09
XS Rating Curve= 0 ,0
Exp/Cntr=0.3,0.1

Type RM Length L Ch R = 1 ,21137.24,501.13,500,495.97
Node Name=1045
XS GIS Cut Line= 3
2419906.29035603284701.3672008512419406.86189294284703.389834598
2418906.86650185284705.414764941
#Sta/Elev= 30
       0   543.4   39.17  539.98   55.49  535.97   71.81  533.57  117.51  528.78
  150.16  526.29  202.38  523.04  238.29  522.53  267.67  518.71   319.9  515.72
  362.33  514.66  421.09  512.02  453.73   511.8  473.32  510.55  494.46  510.61
  504.43  510.28  505.97  510.25  551.72  510.81  587.67   511.8  600.74  512.96
  630.15  513.41  643.22  514.25  649.76  513.95   666.1  515.67  705.32  518.42
  734.73     522  787.02  524.35   839.3  529.28  907.93   531.2  999.43  535.02
#Mann= 3 , 0 , 0
       0     .12       0  494.46    .045       0  504.43     .12       0
Bank Sta=494.46,504.43
XS Rating Curve= 0 ,0
Exp/Cntr=0.3,0.1

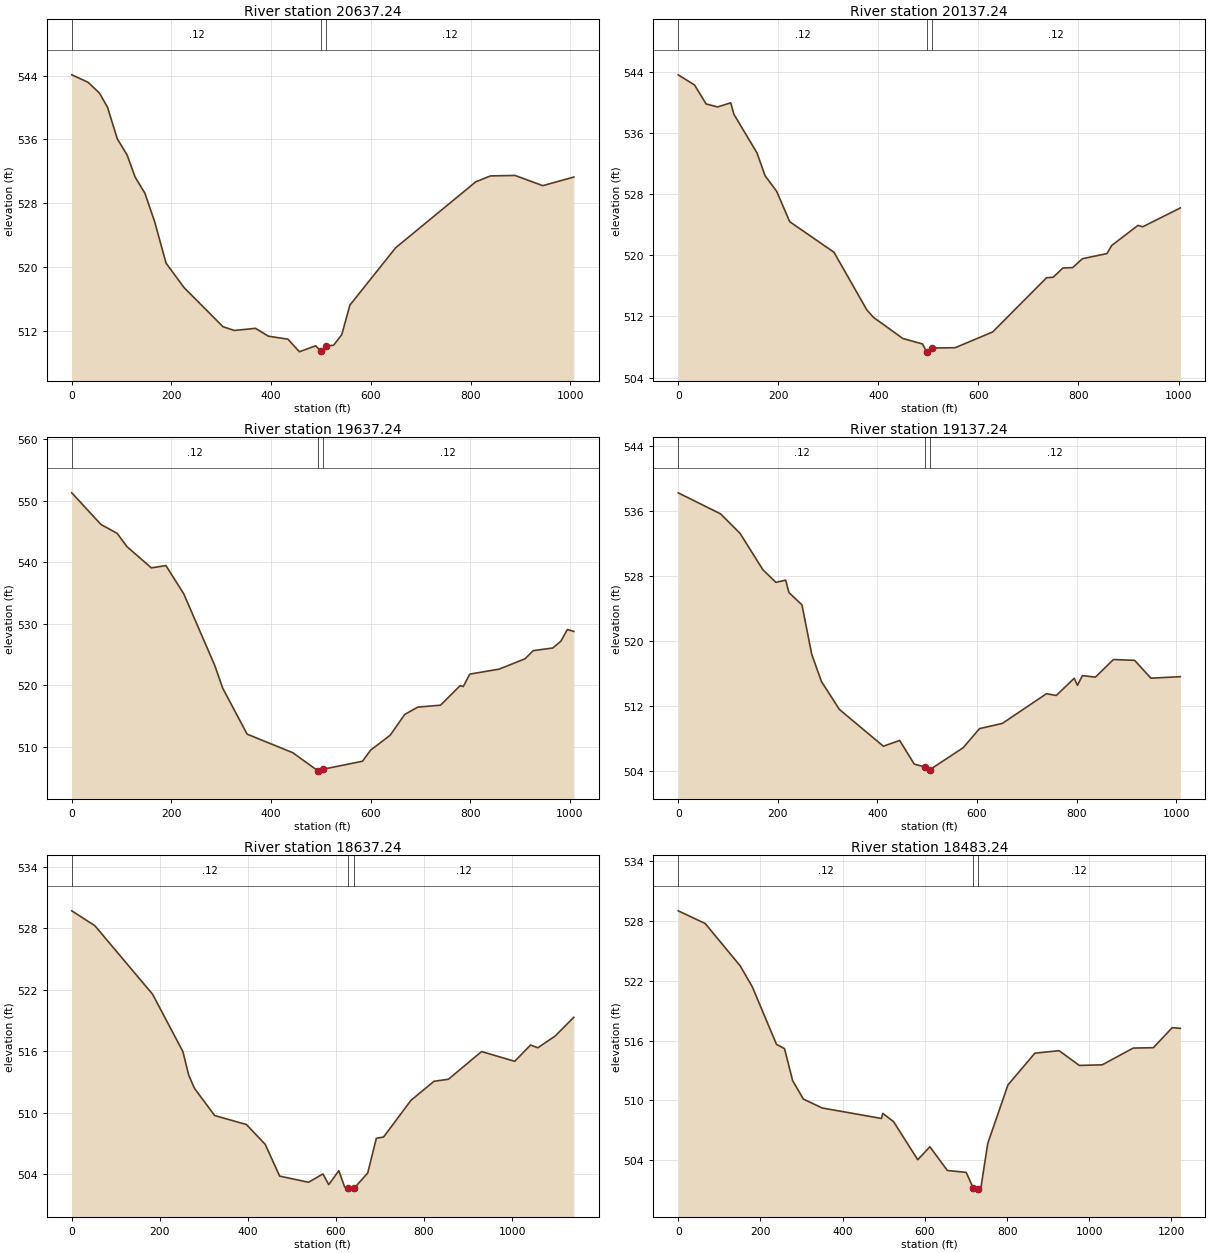
Type RM Length L Ch R = 1 ,20637.24,500.38,500,497.28
Node Name=1046
XS GIS Cut Line= 3
2419846.57787703284170.6956900212419342.76326786284212.384911105
2418842.76361169284253.758516014
#Sta/Elev= 30
       0   544.1   32.62  543.17   55.45  541.82   71.75  540.03   91.32  536.08
  110.89  534.07   127.2  531.27  146.77  529.26  166.34  525.68  189.17   520.5
  225.05  517.45  303.32  512.53  326.15  512.06  368.55  512.33  394.64  511.34
  433.78  510.97  456.61  509.39  489.23  510.14  500.53  509.43  502.28  509.22
  510.51  510.11  525.21  510.21  541.61  511.53     558  515.24  649.82  522.43
   810.5  530.69  840.01  531.43  889.19  531.49  944.94  530.21 1007.24  531.29
#Mann= 3 , 0 , 0
       0     .12       0  500.53    .045       0  510.51     .12       0
Bank Sta=500.53,510.51
XS Rating Curve= 0 ,0
Exp/Cntr=0.3,0.1

Type RM Length L Ch R = 1 ,20137.24,500.96,500,497.95
Node Name=1047
XS GIS Cut Line= 3
2419803.66785786283656.2009841052419307.22068803283726.759241939
2418810.10718094 283797.41231586
#Sta/Elev= 30
       0   543.6   32.77  542.26   55.72  539.79   78.66   539.4  104.88  539.94
  111.43  538.42  157.31   533.4   173.7  530.39  196.64  528.37  222.86  524.39
  311.35  520.39   376.9  512.86  390.01  511.89     449  509.11  488.33   508.4
  496.34  507.39  498.16   507.2  506.54  507.86   553.6  507.91  628.59  509.97
  736.19  517.06  749.23  517.12  768.79  518.33  788.36  518.39  807.92  519.55
  856.83  520.22  866.61  521.29  918.77   523.9  928.56  523.73 1003.55  526.19
#Mann= 3 , 0 , 0
       0     .12       0  496.34    .045       0  506.54     .12       0
Bank Sta=496.34,506.54
XS Rating Curve= 0 ,0
Exp/Cntr=0.3,0.1

Type RM Length L Ch R = 1 ,19637.24,500.65,500,497.44
Node Name=1048
XS GIS Cut Line= 3
 2419770.0117572283140.901489764 2419279.8234331283233.922301099
2418779.39923711283328.885365769
#Sta/Elev= 30
       0  551.26    58.7  546.11   91.31  544.66  110.87  542.51  159.79  539.06
  189.14  539.43  225.01  534.82  286.97  523.23  303.28  519.47  352.19  512.02
   443.5  509.02  493.95  506.09  495.68  506.01  503.94  506.31  583.83  507.62
  600.15  509.42  639.33  511.84  668.72  515.23  694.84  516.42  740.55  516.73
  779.73   519.9  786.26  519.77  799.32  521.78   858.1  522.59  910.34  524.28
  926.66   525.6  965.84  526.03  982.17  527.13  995.23  529.03 1008.29  528.73
#Mann= 3 , 0 , 0
       0     .12       0  493.95    .045       0  503.94     .12       0
Bank Sta=493.95,503.94
XS Rating Curve= 0 ,0
Exp/Cntr=0.3,0.1

Type RM Length L Ch R = 1 ,19137.24,477.97,500,510.79
Node Name=1049
XS GIS Cut Line= 3
2419671.14154811282639.7325446012419184.58445036282756.357639432
2418690.40663294282874.809830353
#Sta/Elev= 30
       0  538.28   85.02  535.69  124.27  533.28  170.05   528.8  196.21  527.25
  215.83  527.52  222.37  525.99  248.53  524.48  268.16  518.38  287.78  515.02
  323.75  511.59  412.04  507.06  444.75  507.77  474.18  504.85  495.04  504.51
  503.62  503.99  505.06  504.15  572.47  506.88  605.25  509.23  651.15  509.87
  739.67  513.53  759.35  513.31  795.41  515.43  801.97  514.56   811.8  515.76
  838.03  515.57   874.1  517.74  916.72  517.64   949.5  515.44 1008.52  515.63
#Mann= 3 , 0 , 0
       0     .12       0  495.04    .045       0  505.06     .12       0
Bank Sta=495.04,505.06
XS Rating Curve= 0 ,0
Exp/Cntr=0.3,0.1

Type RM Length L Ch R = 1 ,18637.24,153.85,154,153.86
Node Name=1050
XS GIS Cut Line= 3
2419634.46708077282424.0190652762419004.60580769282335.125870347
2418505.32596636 282264.66177243
#Sta/Elev= 30
       0  529.71   52.46  528.26  183.62  521.57  252.47  515.97  265.59  513.68
  278.71  512.39  324.61  509.74  396.74  508.86  439.37  506.93  472.16  503.83
  537.74  503.23  570.53  504.04  583.64     503  606.59  504.36  619.71  502.77
  628.19  502.63  629.55  502.56  641.86  502.67  672.12  504.13  691.77  507.52
  708.14  507.64  770.35  511.22  822.73  513.08  855.48  513.28  930.78  515.98
 1006.09  515.03 1042.11  516.62 1058.48  516.35 1097.77  517.49 1140.33  519.33
#Mann= 3 , 0 , 0
       0     .12       0  628.19    .045       0  641.86     .12       0
Bank Sta=628.19,641.86
XS Rating Curve= 0 ,0
Exp/Cntr=0.3,0.1

Type RM Length L Ch R = 1 ,18483.24,335.18,346,352.54
Node Name=1051
XS GIS Cut Line= 3
 2419637.9037537282408.5988205222418946.36248586 282195.92404902
 2418470.3883722282049.544420525
#Sta/Elev= 30
       0  529.01   65.48  527.74  150.59   523.5  180.06   521.4  238.99  515.62
  258.63  515.18  278.27  511.98  304.46  510.12  350.29  509.23  494.34  508.18
  497.61  508.69   523.8  507.86  582.73  504.04   612.2  505.34  654.76  502.96
  700.59  502.77  717.92  501.18  720.23  501.09  728.75  501.09  736.61   501.3
  752.99  505.67  802.13  511.54  867.66  514.73  926.63  514.98  975.77   513.5
 1031.46  513.56 1106.81  515.24 1155.96  515.28 1201.82  517.29 1221.48  517.22
#Mann= 3 , 0 , 0
       0     .12       0  717.92    .045       0  728.75     .12       0
Bank Sta=717.92,728.75
XS Rating Curve= 0 ,0
Exp/Cntr=0.3,0.1

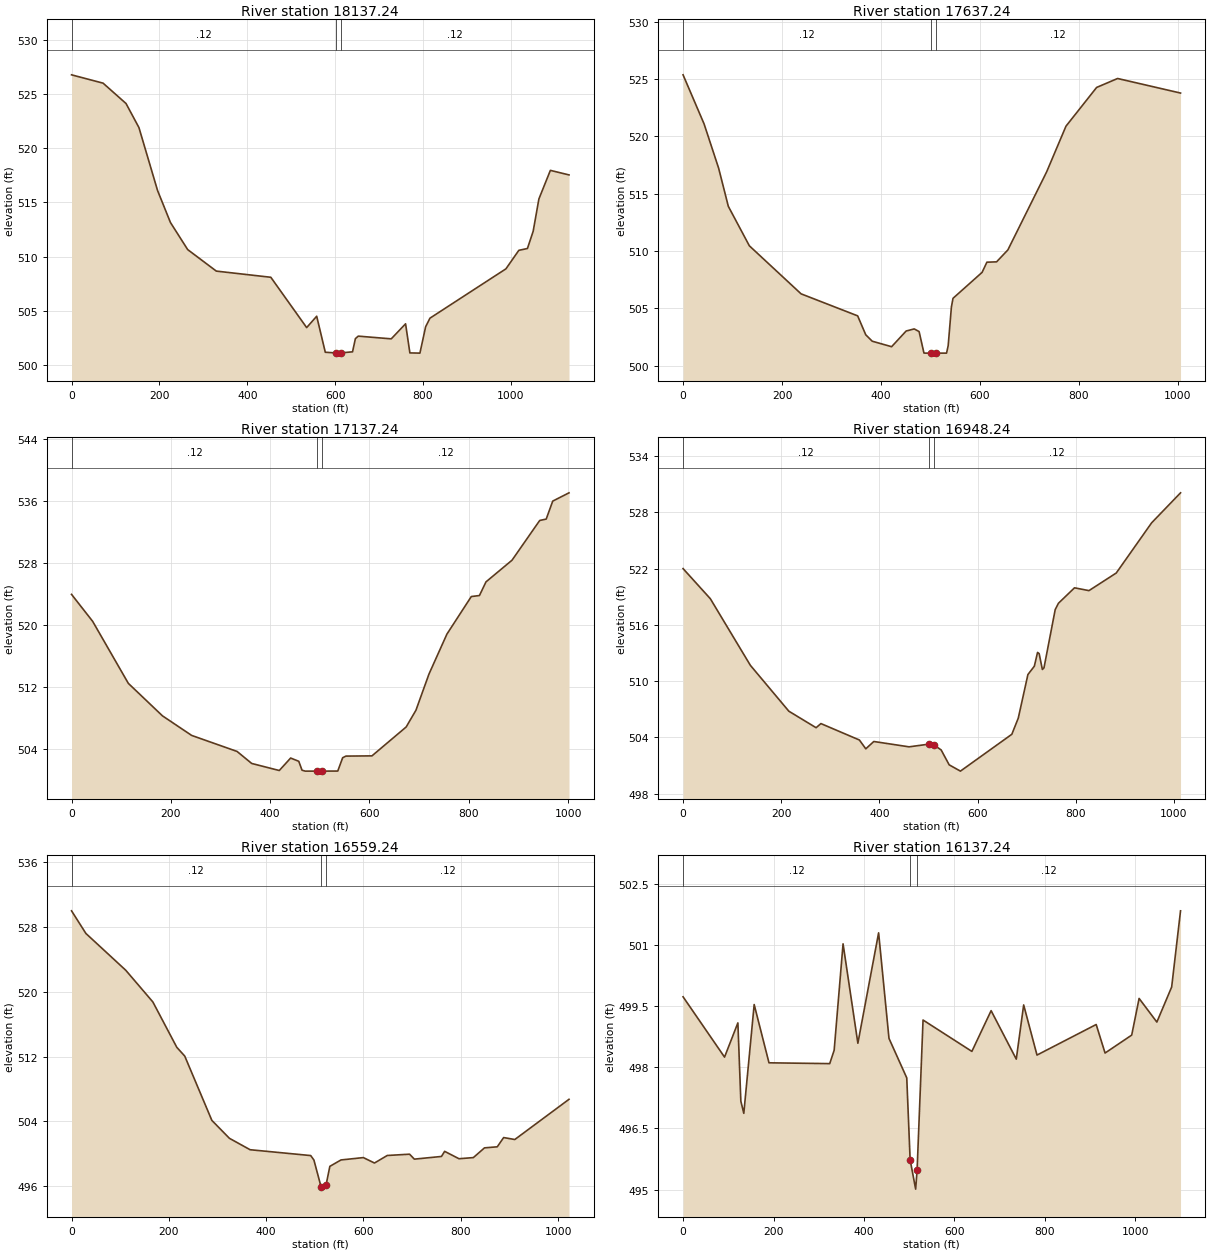
Type RM Length L Ch R = 1 ,18137.24,489.8,500,507.8
Node Name=1052
XS GIS Cut Line= 3
2419651.52544561282380.7005823552419154.05006261 282032.94766894
2418723.44724928281731.941381186
#Sta/Elev= 30
       0  526.79   71.79  526.02     124  524.14  153.37  521.92   195.8   516.1
  225.17  513.14  264.33  510.64  329.59  508.65   453.6  508.08  535.18  503.43
  558.02  504.48   577.6  501.15  602.06  501.09  612.22  501.09   639.6  501.19
  646.13  502.41  652.66  502.64  727.71  502.39  760.34  503.78  770.13  501.09
  792.98  501.07  806.03  503.51  815.82   504.3  988.77  508.86 1018.14  510.57
 1037.72  510.74 1050.77  512.33 1063.82  515.32 1089.93  517.96 1132.35  517.54
#Mann= 3 , 0 , 0
       0     .12       0  602.06    .045       0  612.22     .12       0
Bank Sta=602.06,612.22
XS Rating Curve= 0 ,0
Exp/Cntr=0.3,0.1

Type RM Length L Ch R = 1 ,17637.24,491.46,500,508.54
Node Name=1053
XS GIS Cut Line= 3
2419881.53712469282188.4365311862419566.61813511281791.739161849
2419256.33988428281400.888237521
#Sta/Elev= 30
       0  525.36   42.48  521.08   71.89  517.22    91.5  513.89  133.98  510.45
  238.55  506.26  352.92  504.34  369.26  502.69  382.33  502.13  421.54  501.65
  450.95  503.02  467.29   503.2  477.09  502.97  486.89   501.1  490.16  501.09
  501.45  501.09  511.55  501.09  532.59  501.09  535.86  501.74  542.38  505.11
  545.64  505.87  604.35  508.13  614.14  509.02  633.71  509.05  656.54  510.09
  734.82  516.89  773.96  520.88  835.93  524.26  878.33  525.04 1005.54  523.77
#Mann= 3 , 0 , 0
       0     .12       0  501.45    .045       0  511.55     .12       0
Bank Sta=501.45,511.55
XS Rating Curve= 0 ,0
Exp/Cntr=0.3,0.1

Type RM Length L Ch R = 1 ,17137.24,179.49,189,197.92
Node Name=1054
XS GIS Cut Line= 3
2420203.44888245282033.9568532712420014.58114994281570.844590515
2419825.08874677281106.201490939
#Sta/Elev= 30
       0  523.91    42.5  520.43  114.41  512.42  183.06  508.23   241.9   505.7
  333.43  503.63  362.85  502.08  418.42  501.17   441.3  502.78  457.65  502.36
  464.19  501.21  470.72  501.09  495.15  501.09  505.15  501.09  536.22   501.1
  546.06  502.82  552.62  503.03  605.09  503.06  673.97  506.79  693.65  508.95
  719.89  513.62  755.96  518.77  805.16  523.63  821.56  523.76  834.68  525.52
  887.15  528.32  942.91  533.45  956.03  533.63  969.15  535.95 1001.94  537.02
#Mann= 3 , 0 , 0
       0     .12       0  495.15    .045       0  505.15     .12       0
Bank Sta=495.15,505.15
XS Rating Curve= 0 ,0
Exp/Cntr=0.3,0.1

Type RM Length L Ch R = 1 ,16948.24,335.9,389,345.53
Node Name=1055
XS GIS Cut Line= 3
2420233.01870519282026.8886259352420191.54733144 281522.40439868
2420149.97884503 281016.73743102
#Sta/Elev= 30
       0  522.01   55.52   518.8  137.16  511.69  215.54   506.8  271.05  505.04
  280.85  505.48  359.23  503.73  372.29  502.79  388.62  503.57  460.47     503
  501.17  503.29  511.19   503.2  525.83  502.67  542.19  501.08  565.11  500.41
  669.85  504.34  682.95  506.06  702.59  510.71  715.68   511.6  722.23  513.07
   725.5  512.94  732.05  511.25  735.32  511.42  758.23  517.64  764.78  518.31
  797.52  519.96  826.98  519.66  882.62  521.54  954.64  526.89 1013.56  530.09
#Mann= 3 , 0 , 0
       0     .12       0  501.17    .045       0  511.19     .12       0
Bank Sta=501.17,511.19
XS Rating Curve= 0 ,0
Exp/Cntr=0.3,0.1

Type RM Length L Ch R = 1 ,16559.24,422,422,405.14
Node Name=1056
XS GIS Cut Line= 3
2420416.59543778282024.2373845132420491.83642903281511.898842275
 2420565.1673191281012.567163765
#Sta/Elev= 30
       0  529.97    29.5  527.18  111.43  522.64  167.15  518.73  216.31  513.14
   232.7  512.05  288.41  504.12  324.47  501.91  367.07   500.5  491.61  499.78
  498.17  499.23  513.01   495.9  517.83  495.64  523.32   496.2  530.94  498.45
  553.88  499.24  599.76  499.53   622.7  498.86  648.92  499.79   694.8  499.95
  704.63  499.34  760.35  499.67   766.9   500.3   796.4  499.39  825.89  499.53
  848.83  500.73  875.05  500.86  888.16     502   911.1  501.76 1022.52  506.72
#Mann= 3 , 0 , 0
       0     .12       0  513.01    .045       0  523.32     .12       0
Bank Sta=513.01,523.32
XS Rating Curve= 0 ,0
Exp/Cntr=0.3,0.1

Type RM Length L Ch R = 1 ,16137.24,520.68,500,464.88
Node Name=1057
XS GIS Cut Line= 3
2421015.96497394282062.6894073492420854.19397202281578.080140352
2420667.73699586281019.520233855
#Sta/Elev= 30
       0  499.73    91.7  498.25  121.17  499.09  127.72  497.17  134.27  496.87
   157.2  499.54  189.95  498.11  324.22  498.09  334.05  498.42   353.7  501.03
  386.45  498.59   432.3   501.3  455.22  498.71  494.52  497.74  501.97  495.73
  514.17  495.01  517.37  495.47  530.53  499.16  638.48  498.39  681.01  499.39
  736.63   498.2  752.98  499.53  782.43   498.3  913.28  499.05  932.91  498.35
   991.8  498.79 1008.16  499.69 1047.41  499.11 1080.13  499.97 1099.76  501.84
#Mann= 3 , 0 , 0
       0     .12       0  501.97    .045       0  517.37     .12       0
Bank Sta=501.97,517.37
XS Rating Curve= 0 ,0
Exp/Cntr=0.3,0.1

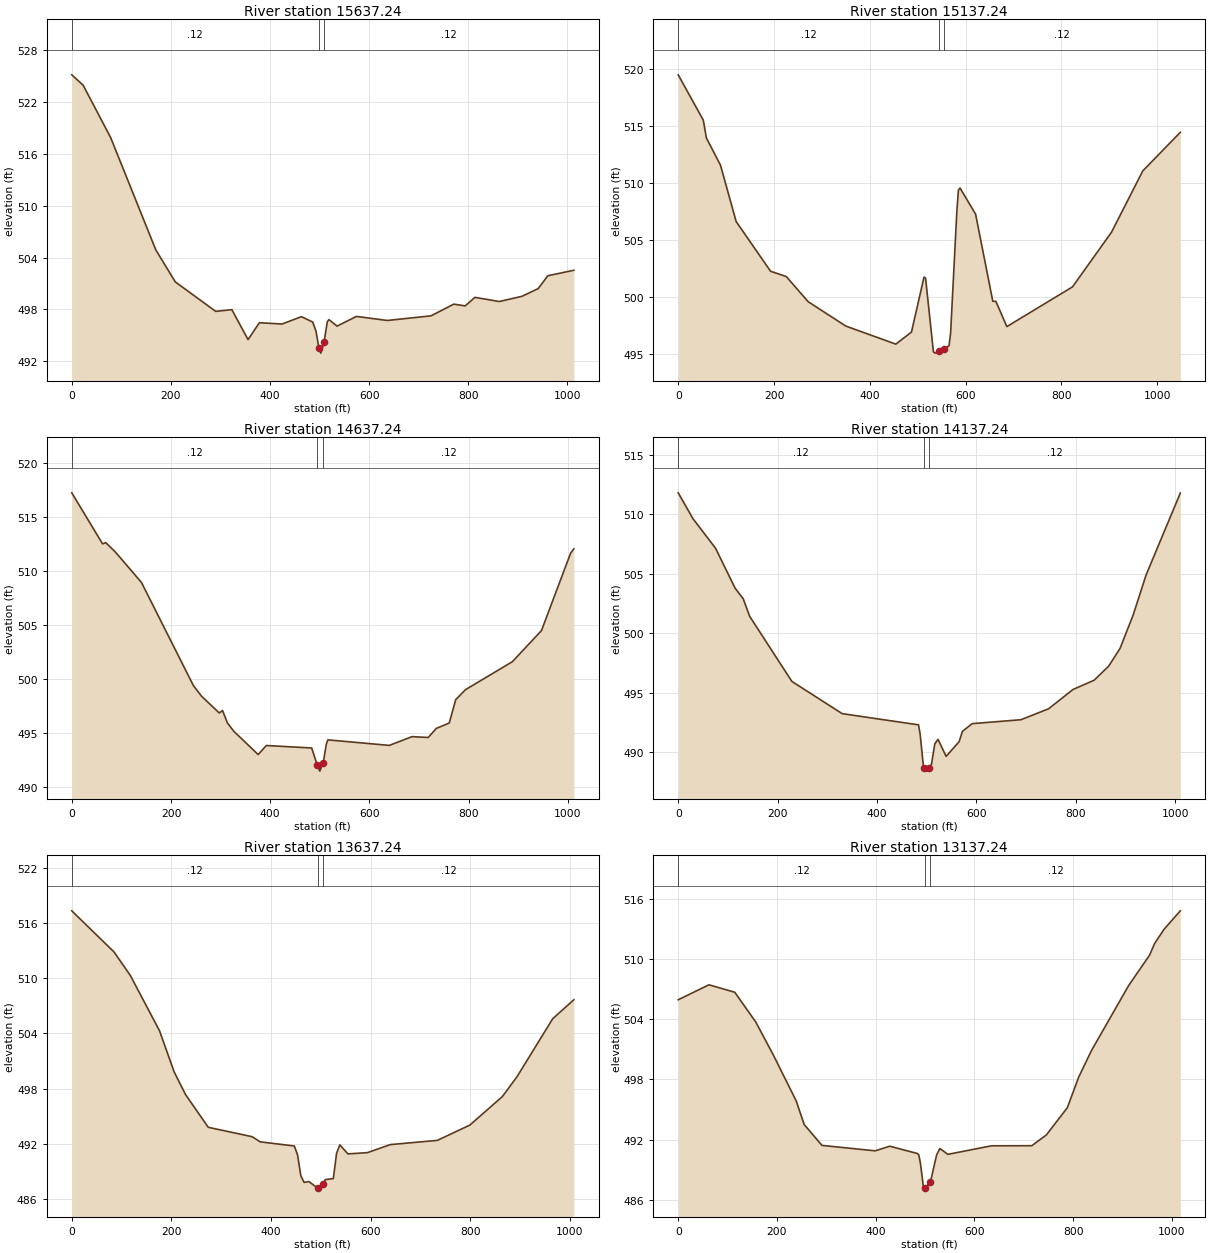
Type RM Length L Ch R = 1 ,15637.24,484.79,500,503.57
Node Name=1058
XS GIS Cut Line= 3
2421564.71289219281569.6805508582421178.67527844281247.817021355
2420786.48872685 280920.82686168
#Sta/Elev= 30
       0   525.1   22.85  523.91   78.33  517.87  169.71  504.87  208.88  501.19
  290.47  497.78  323.11  497.98  355.75  494.52  378.59  496.47  424.29  496.32
  463.45  497.17   486.3  496.55  492.82   495.5  498.87  493.55  502.61  492.96
  509.01   494.2  515.71  496.59  518.98  496.83  535.35  496.08  574.63   497.2
  636.82  496.73  725.19  497.27  771.02  498.62  793.93  498.41  813.57   499.4
  862.67  498.92  908.49  499.52  941.23  500.41  960.87   501.9 1013.24  502.53
#Mann= 3 , 0 , 0
       0     .12       0  498.87    .045       0  509.01     .12       0
Bank Sta=498.87,509.01
XS Rating Curve= 0 ,0
Exp/Cntr=0.3,0.1

Type RM Length L Ch R = 1 ,15137.24,484.44,500,503.1
Node Name=1059
XS GIS Cut Line= 3
2421789.96572253281345.4618391842421485.35773595280888.709471852
2421208.44326353280473.483268186
#Sta/Elev= 30
       0  519.49   52.29  515.51   58.82  513.94   88.23  511.55  120.91   506.6
  192.81  502.23  225.49  501.77  271.24  499.56  349.67  497.42  454.24  495.83
  486.92  496.89  513.06  501.72  516.33  501.63  532.67  495.16  535.93  495.04
  543.78  495.21  554.04  495.38  565.32  495.69  568.58  496.79  581.63  507.52
  584.89  509.34  588.15  509.55  620.77  507.25  656.65   499.6  663.18  499.58
  686.01  497.37  823.02  500.86  904.57  505.67  969.81  511.05  1048.1  514.44
#Mann= 3 , 0 , 0
       0     .12       0  543.78    .045       0  554.04     .12       0
Bank Sta=543.78,554.04
XS Rating Curve= 0 ,0
Exp/Cntr=0.3,0.1

Type RM Length L Ch R = 1 ,14637.24,517.83,500,473.6
Node Name=1060
XS GIS Cut Line= 3
2422074.52388044281271.6860681032421949.85844736280787.589595348
2421822.15824345 280291.70705694
#Sta/Elev= 30
       0  517.22   62.08   512.5   68.61  512.61   88.22  511.73  140.49  508.93
  245.04   499.4  261.38  498.42  297.32  496.86  303.86  497.09  313.66  495.94
  326.73  495.16  375.73  493.01  392.07  493.85  483.55  493.62  494.86  492.02
  499.89  491.48  506.95  492.26  512.94  493.95   516.2  494.37  640.14  493.86
   685.8  494.67  718.41  494.59  734.72  495.43  760.81  495.93  773.86  498.09
  793.43  499.01  888.01   501.6  946.72  504.48 1005.43  511.64 1011.95  512.04
#Mann= 3 , 0 , 0
       0     .12       0  494.86    .045       0  506.95     .12       0
Bank Sta=494.86,506.95
XS Rating Curve= 0 ,0
Exp/Cntr=0.3,0.1

Type RM Length L Ch R = 1 ,14137.24,498.42,500,496.48
Node Name=1061
XS GIS Cut Line= 3
2422705.59643719280763.913461611 2422291.5555986280483.621699348
2421868.69030261280197.355867684
#Sta/Elev= 30
       0  511.79   29.41  509.63   75.16  507.13  114.38  503.78  130.72  502.89
  143.79  501.41  228.75  495.94  330.06  493.23  483.65  492.29  486.92  491.52
  493.46  488.82  495.06  488.63  499.99   488.4  505.33  488.68  509.81  488.99
  516.36  490.68  522.91  491.07  539.27  489.64  565.46  490.88  572.01  491.74
  591.65  492.39  689.85  492.72   745.5  493.64   794.6  495.26  837.15  496.04
  866.61  497.23  889.53  498.73  915.71  501.52   941.9   504.9 1010.64  511.77
#Mann= 3 , 0 , 0
       0     .12       0  495.06    .045       0  505.33     .12       0
Bank Sta=495.06,505.33
XS Rating Curve= 0 ,0
Exp/Cntr=0.3,0.1

Type RM Length L Ch R = 1 ,13637.24,487.68,500,488.69
Node Name=1062
XS GIS Cut Line= 3
2423011.21492045280363.4247612662422586.06288362280101.883289605
2422152.47516811 279835.15252386
#Sta/Elev= 30
       0  517.31   84.82  512.85  117.45  510.31  176.17   504.3  205.54  499.84
  228.37  497.38  274.05  493.82  362.13   492.8  378.45  492.24  446.96  491.79
  453.48  490.81  460.01  488.55  466.53  487.84  476.32  487.93  494.57  487.19
  499.16  487.11  504.52  487.62  508.95  488.14  525.26  488.26  531.79  491.01
  538.32  491.91  554.63  490.93  593.79  491.07  639.48  491.94  734.11   492.4
  799.37  494.06  864.64  497.15  894.01   499.3   965.8   505.6 1008.22  507.66
#Mann= 3 , 0 , 0
       0     .12       0  494.57    .045       0  504.52     .12       0
Bank Sta=494.57,504.52
XS Rating Curve= 0 ,0
Exp/Cntr=0.3,0.1

Type RM Length L Ch R = 1 ,13137.24,395.34,406,407.03
Node Name=1063
XS GIS Cut Line= 3
 2423314.9472526279964.6660443542422864.65090911279738.954881608
2422405.81225985279508.962231353
#Sta/Elev= 30
       0  505.93   62.14  507.42  114.48  506.68     157  503.72  192.98   500.4
  238.77  495.89  255.12  493.52   291.1  491.44  399.03   490.9  428.47  491.36
  484.07  490.64  487.34  490.48  490.62  489.64  497.16  487.09   499.6  487.19
  510.92  487.82  523.31  490.48  529.85  491.13   546.2  490.55  634.46   491.4
  716.19  491.41  745.62  492.48  788.11  495.19     811  498.22  837.15  500.89
  912.34  507.35  954.84  510.38  964.65  511.51  984.26  512.96 1016.95  514.78
#Mann= 3 , 0 , 0
       0     .12       0   499.6    .045       0  510.92     .12       0
Bank Sta=499.6,510.92
XS Rating Curve= 0 ,0
Exp/Cntr=0.3,0.1

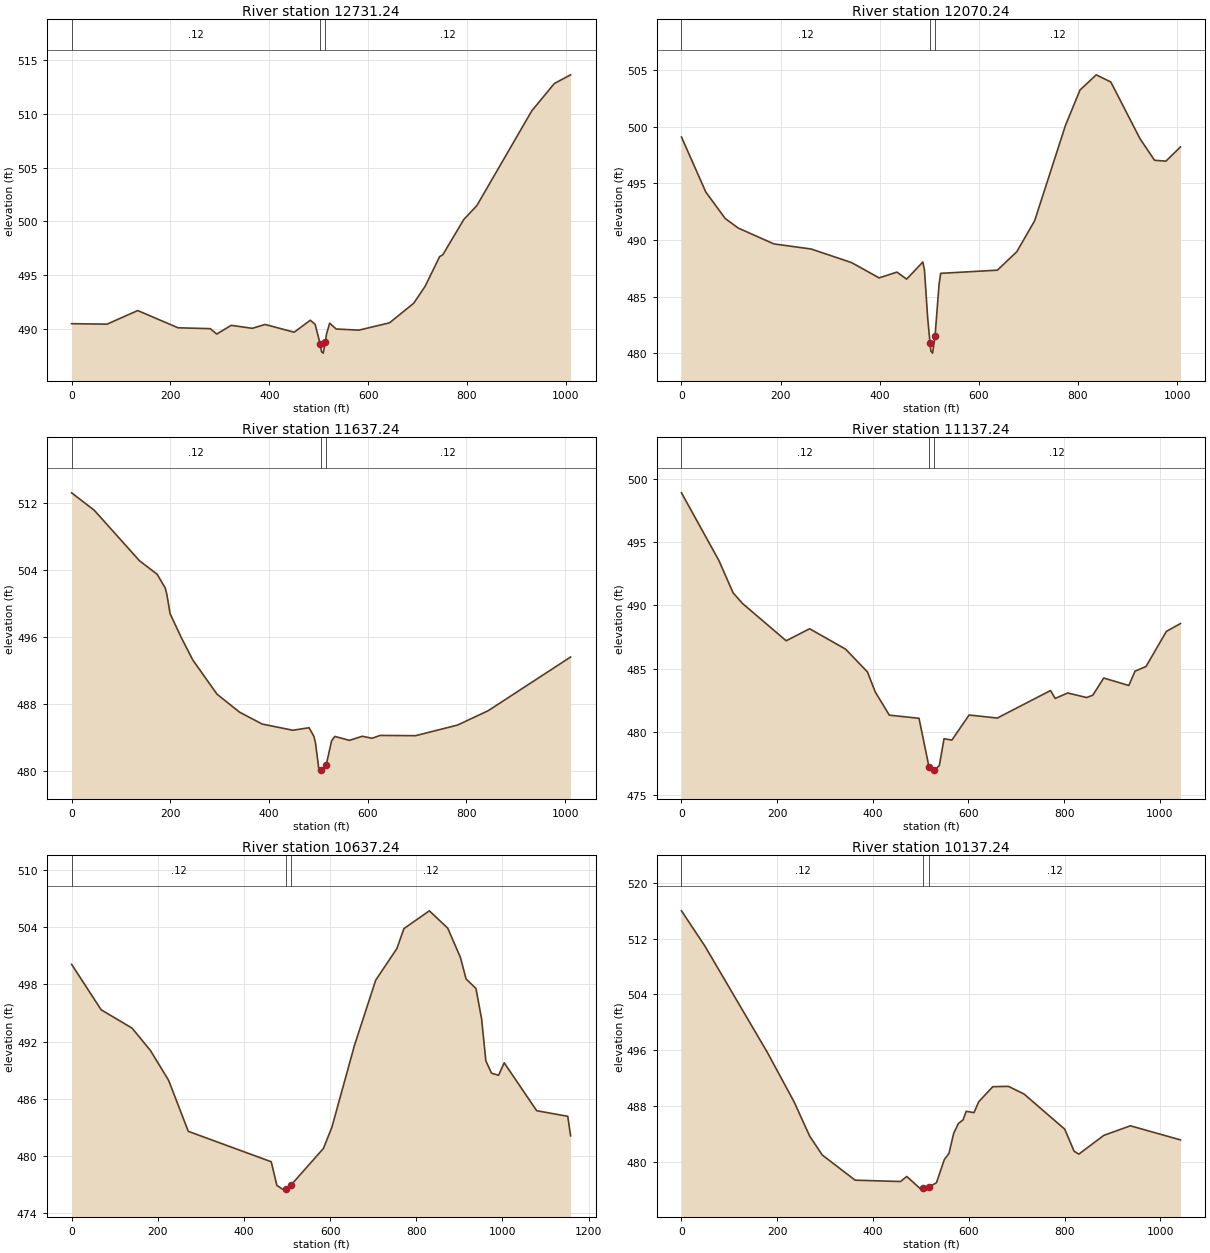
Type RM Length L Ch R = 1 ,12731.24,666.71,661,646.61
Node Name=1064
XS GIS Cut Line= 3
2423473.45349728279744.5208153582423083.93393511 279416.72357069
2422700.85169603279094.343966097
#Sta/Elev= 30
       0  490.51    71.8  490.47   133.8  491.73  215.39  490.13  280.65  490.05
  293.71  489.55  323.08  490.36   365.5  490.08  391.61  490.44  450.35  489.72
  482.99  490.83  492.78  490.46  502.75  488.67  505.83  487.91  509.09  487.78
  513.67  488.84  515.64  489.51  522.18  490.56  535.27  490.02  581.09  489.91
  643.26  490.59  692.35  492.41  715.26  493.97  744.71  496.73  751.25  496.91
  793.79  500.19  819.97  501.46  931.24  510.26  977.05   512.8 1009.77   513.6
#Mann= 3 , 0 , 0
       0     .12       0  502.75    .045       0  513.67     .12       0
Bank Sta=502.75,513.67
XS Rating Curve= 0 ,0
Exp/Cntr=0.3,0.1

Type RM Length L Ch R = 1 ,12070.24,439.26,433,422.76
Node Name=1065
XS GIS Cut Line= 3
2423846.44422111279028.3322871032423369.94222136278856.606252611
2422899.48253235278687.057379097
#Sta/Elev= 30
       0  499.09   49.02  494.24   88.23   491.9  114.37  491.06  186.26  489.66
  261.42  489.21  343.11  488.01  398.67  486.66  434.61  487.17  454.22  486.55
   486.9  488.06  490.16  487.34   496.7  483.09   501.5  480.87  503.23  480.19
   506.5  480.02  511.46  481.49  519.58  486.07  522.84  487.06  637.24  487.34
  676.46  488.97  712.42   491.7  774.52  500.11  803.93  503.24  836.62  504.58
  866.04  503.95  924.87  498.95  954.28  497.04  977.16  496.96 1006.58  498.22
#Mann= 3 , 0 , 0
       0     .12       0   501.5    .045       0  511.46     .12       0
Bank Sta=501.5,511.46
XS Rating Curve= 0 ,0
Exp/Cntr=0.3,0.1

Type RM Length L Ch R = 1 ,11637.24,482.9,500,510.76
Node Name=1066
XS GIS Cut Line= 3
2423959.55849619278490.2480614332423450.25177203278454.863289684
2422950.90762636278420.170773774
#Sta/Elev= 30
       0  513.24   45.82  511.16  137.45  505.12  173.45  503.49  189.81  501.84
  193.09  501.07  199.63  498.77  222.54  495.89  245.45  493.25  294.54  489.16
  340.36     487  386.17  485.58  448.35  484.84  481.08  485.14   490.9  484.12
  494.17  483.32  500.72  480.32  503.99  479.95  505.42  480.05   515.7  480.65
  526.89  483.59  533.44   484.1  562.88  483.63  589.05  484.12  608.68  483.88
  625.04  484.22  697.01  484.19  782.07  485.46  844.23  487.18 1011.08   493.6
#Mann= 3 , 0 , 0
       0     .12       0  505.42    .045       0   515.7     .12       0
Bank Sta=505.42,515.7
XS Rating Curve= 0 ,0
Exp/Cntr=0.3,0.1

Type RM Length L Ch R = 1 ,11137.24,471.51,500,498.81
Node Name=1067
XS GIS Cut Line= 3
 2423998.4793501 278231.952646272423541.09739086277978.721197352
2423085.70788169277726.592764601
#Sta/Elev= 30
       0  498.88   78.42  493.52  107.83  490.99  127.43  490.15  218.92   487.2
  267.94  488.15  343.09  486.54  388.84  484.74  405.17  483.16  434.58  481.33
  496.66  481.08   517.6  477.23  526.08  476.91  528.09  476.96  539.17  477.35
     549  479.47  565.36  479.36  601.38  481.34   660.3   481.1  771.61  483.27
  781.43  482.65  807.62  483.08  846.91  482.72     860   482.9  882.92  484.26
   935.3  483.67  948.39   484.8  971.31  485.17 1013.87  487.94 1043.33  488.56
#Mann= 3 , 0 , 0
       0     .12       0   517.6    .045       0  528.09     .12       0
Bank Sta=517.6,528.09
XS Rating Curve= 0 ,0
Exp/Cntr=0.3,0.1

Type RM Length L Ch R = 1 ,10637.24,513.77,500,486.56
Node Name=1068
XS GIS Cut Line= 3
2424194.36609744278066.0878205152423807.15427344277745.877831027
2423301.92562512 277328.07223618
#Sta/Elev= 30
       0  500.12   68.52  495.34   140.3  493.41  182.71  491.07  225.13  487.92
  270.81  482.55  463.31  479.35  476.36  476.86  489.41  476.47  496.56  476.51
  509.82  476.93  584.41  480.75  604.08  482.98  656.53   491.6   705.7  498.45
  754.87  501.78  771.26  503.88  830.26  505.75  872.88  503.93  902.38  500.85
  915.49  498.58  938.44  497.58  951.55  494.38  961.38  489.97   974.5  488.67
  990.89  488.45    1004  489.76 1079.39  484.72 1151.51  484.13 1158.07  482.08
#Mann= 3 , 0 , 0
       0     .12       0  496.56    .045       0  509.82     .12       0
Bank Sta=496.56,509.82
XS Rating Curve= 0 ,0
Exp/Cntr=0.3,0.1

Type RM Length L Ch R = 1 ,10137.24,542.46,548,545.95
Node Name=1069
XS GIS Cut Line= 3
2424361.44089453  277376.82968462423854.24210578  277326.6329346
2423324.37669569277274.192750767
#Sta/Elev= 30
       0  515.97   49.01  510.91  179.69  495.65  235.24   488.6  267.91  483.68
  294.04     481  362.65  477.39   457.4   477.2  470.47  477.92  499.88  476.11
  505.21  476.33   516.9   476.4  532.54  477.03  548.88  480.33  558.68  481.24
  568.48   484.1  578.28  485.51  588.08  486.03  594.61  487.25  610.94  487.07
  620.74  488.62  650.14  490.78  682.81  490.83  715.47  489.73   800.4   484.7
     820  481.54   829.8  481.12  882.07  483.81   937.6  485.18 1042.13  483.16
#Mann= 3 , 0 , 0
       0     .12       0  505.21    .045       0   516.9     .12       0
Bank Sta=505.21,516.9
XS Rating Curve= 0 ,0
Exp/Cntr=0.3,0.1