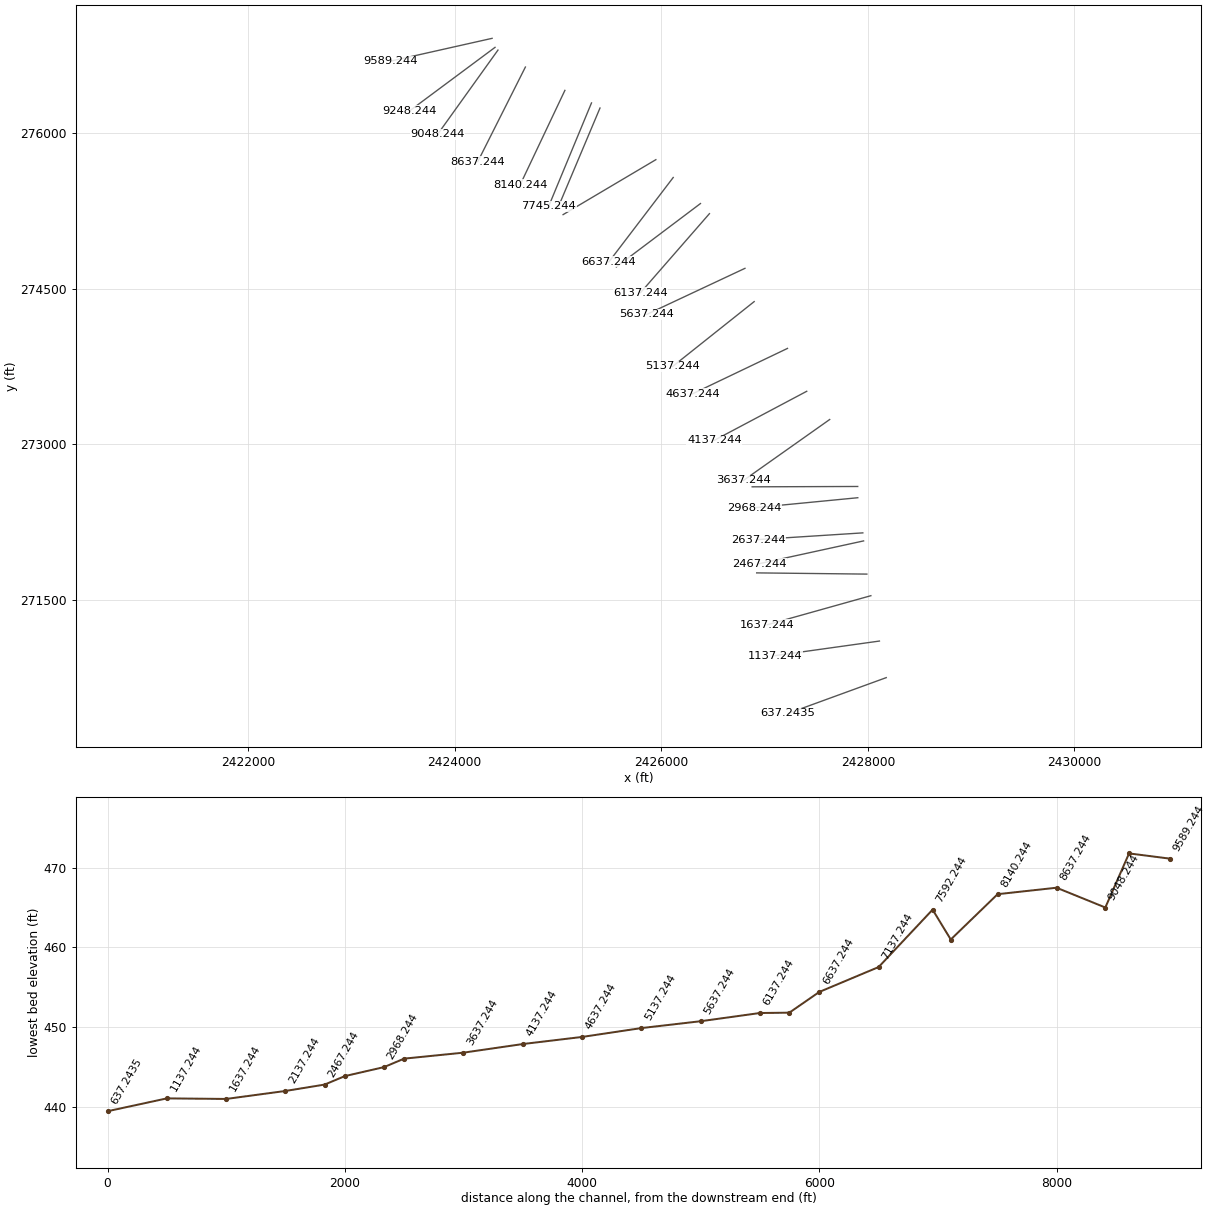
HEC-RAS study NorthForkBullskinRu.prj: NorthForkBullskinRun

--- NorthForkBullskinRu.g01 (geometry) --- (continued)

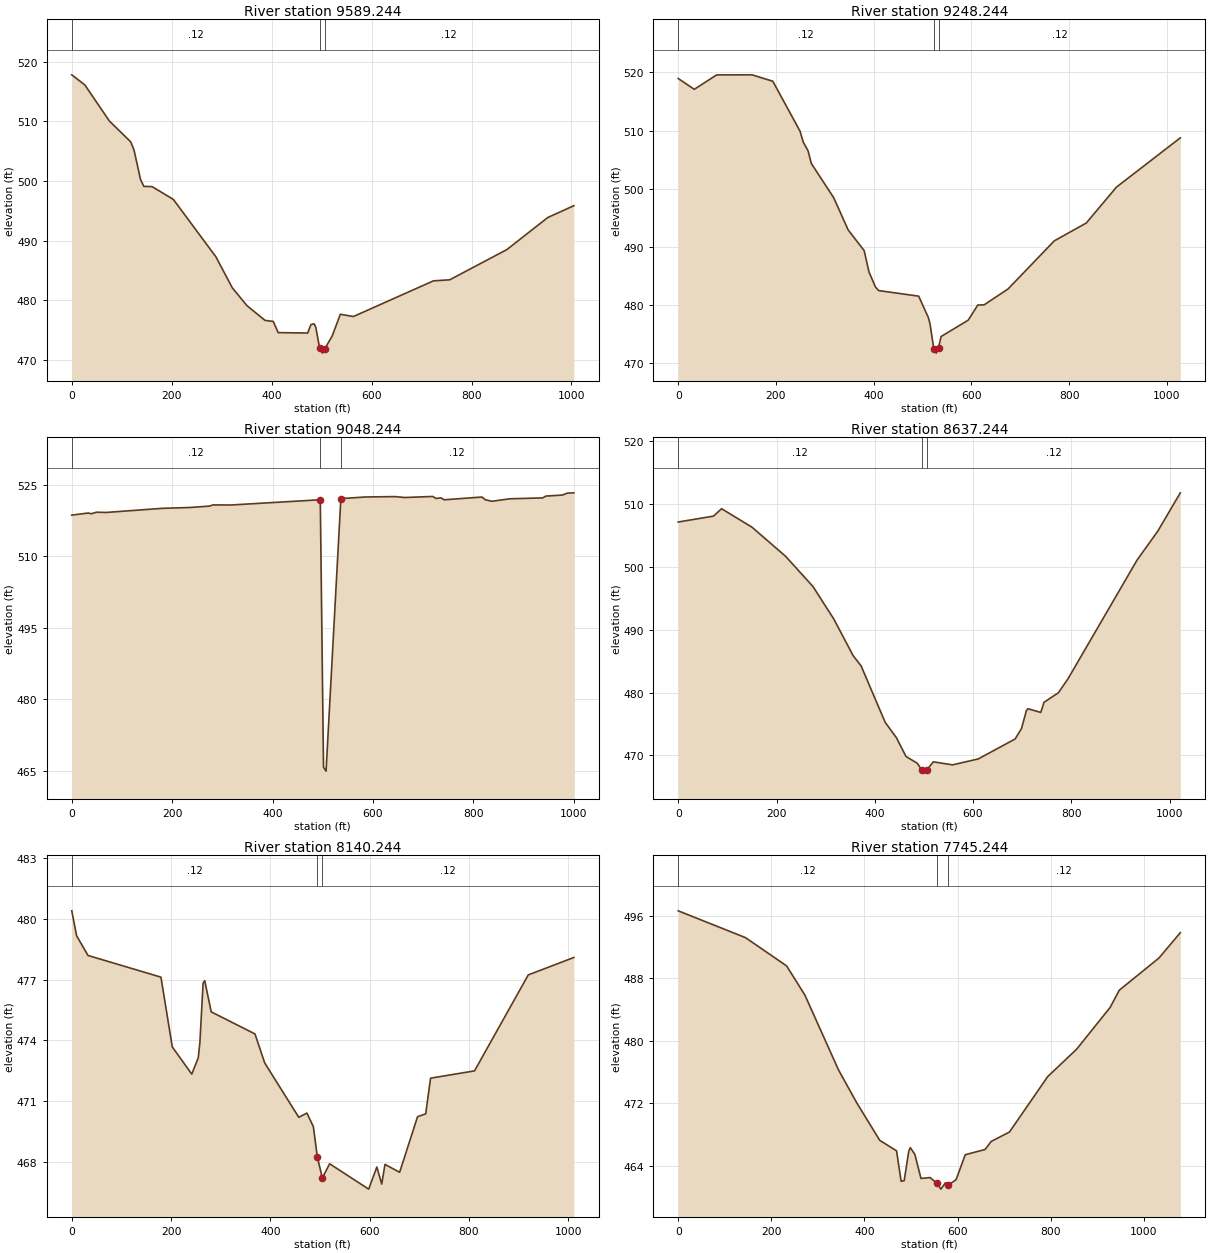
Type RM Length L Ch R = 1 ,9589.244,315.22,341,344.51
Node Name=1070
XS GIS Cut Line= 3
2424363.52848877276918.6764014362423874.08524194276808.965334773
2423383.07834995276698.904203191
#Sta/Elev= 30
       0  517.81   26.23  516.11    75.4  510.05  118.02  506.57  124.58  505.19
  137.69  500.23  144.25   499.1  160.64  499.06  203.26  496.92   288.5  487.28
  321.28  482.08  350.78  479.08  386.85  476.62  403.24  476.45  413.07  474.57
  472.08   474.5  478.64  475.92   485.2  476.04  488.48  475.43  496.01  471.96
  501.59  471.13  506.07  471.81  521.19  474.01  537.53  477.65  563.67  477.27
  723.78  483.25  756.45  483.43  870.81   488.5   952.5  493.87 1004.78  495.86
#Mann= 3 , 0 , 0
       0     .12       0  496.01    .045       0  506.07     .12       0
Bank Sta=496.01,506.07
XS Rating Curve= 0 ,0
Exp/Cntr=0.3,0.1

Type RM Length L Ch R = 1 ,9248.244,190.67,200,209.11
Node Name=1071
XS GIS Cut Line= 3
2424391.88177852276831.455119193 2423967.7002122276516.951483101
2423566.66065994276219.605949193
#Sta/Elev= 30
       0  518.93    32.8  517.07   78.72  519.55  150.87  519.56  193.51  518.46
  249.27  509.88  255.83     508  265.67  506.52  272.23  504.35  318.15  498.46
  347.66  492.94  380.46  489.38   390.3  485.72  403.42  483.16  409.98  482.52
  491.98  481.56  511.66  477.91  514.94  476.92  522.93  472.54  528.06  471.78
   532.7  472.74  537.84  474.63  593.32  477.44   612.9  480.04  625.95  480.07
  674.89   482.8  769.52  491.06  834.78  494.11  896.78  500.29  1027.3  508.74
#Mann= 3 , 0 , 0
       0     .12       0  522.93    .045       0   532.7     .12       0
Bank Sta=522.93,532.7
XS Rating Curve= 0 ,0
Exp/Cntr=0.3,0.1

Type RM Length L Ch R = 1 ,9048.244,398.7,411,409.85
Node Name=1072
XS GIS Cut Line= 3
2424420.32922819276805.156615347 2424128.6408352276399.055721521
2423836.95211411275992.955155775
#Sta/Elev= 30
       0  518.61   32.68  519.05   39.22   518.9   49.02  519.22   68.63  519.17
  179.74  520.03  235.29  520.21  274.51   520.5  281.05  520.75  316.99  520.73
     495  521.83  501.41  465.83  506.48     465  535.95  522.07  584.97  522.41
  643.79  522.49   663.4   522.3  718.95  522.52  725.49   522.1  735.29  522.23
  741.83  521.82  816.99   522.4  823.53  521.84   836.6  521.51  872.55  522.03
  937.91  522.22  944.44   522.6  977.12  522.81  986.93  523.21    1000  523.28
#Mann= 3 , 0 , 0
       0     .12       0     495    .045       0  535.95     .12       0
Bank Sta=495,535.95
XS Rating Curve= 0 ,0
Exp/Cntr=0.3,0.1

Type RM Length L Ch R = 1 ,8637.244,487.7,497,485.94
Node Name=1073
XS GIS Cut Line= 3
2424685.73453727276641.3764311082424460.66904253276195.423582852
 2424225.3647231  275729.1833736
#Sta/Elev= 30
       0  507.17   71.83  508.11   88.15  509.29  150.19  506.34  218.75  501.69
  274.25  496.89  316.69   491.7  355.87  485.89   372.2  484.24  421.17  475.26
  444.03   472.8  463.62  469.81  486.47  468.73  496.15  467.61  499.53  467.48
  505.76  467.66  519.11  468.96  558.28  468.48  610.51  469.42  685.58   472.6
  698.64  474.27  708.43   477.1  711.69  477.42  737.81  476.83  744.33  478.44
  773.71  479.97   793.3   482.2  933.65  501.09  976.08  505.73 1021.78  511.82
#Mann= 3 , 0 , 0
       0     .12       0  496.15    .045       0  505.76     .12       0
Bank Sta=496.15,505.76
XS Rating Curve= 0 ,0
Exp/Cntr=0.3,0.1

Type RM Length L Ch R = 1 ,8140.244,325.49,395,379.88
Node Name=1074
XS GIS Cut Line= 3
2425068.12058352276416.2298997642424853.72042178 275964.69668211
2424634.21889228275502.420047596
#Sta/Elev= 30
       0  480.39     9.8  479.16   32.67  478.19  179.68  477.12  202.55  473.68
  241.76  472.34  254.83  473.14  258.09  473.88  264.63  476.83  267.89  476.95
  280.96  475.41  369.17  474.32  388.77  472.89  457.38  470.21  473.71  470.42
  486.78  469.75  494.89  468.24  504.91  467.22  519.53  467.92  598.26  466.67
  614.66  467.76   624.5  466.92  631.07  467.89  660.59   467.5  696.67  470.24
  713.08  470.38  722.92  472.14  811.49   472.5  919.74  477.23 1011.59  478.09
#Mann= 3 , 0 , 0
       0     .12       0  494.89    .045       0  504.91     .12       0
Bank Sta=494.89,504.91
XS Rating Curve= 0 ,0
Exp/Cntr=0.3,0.1

Type RM Length L Ch R = 1 ,7745.244,123.04,153,135.1
Node Name=1075
XS GIS Cut Line= 3
 2425325.5337826276295.0306670962425109.23073752275774.085514769
2424911.97850735275299.022816598
#Sta/Elev= 30
       0  496.66   144.3  493.23  232.84   489.6  272.19  485.85  344.34  476.26
   383.7  472.03  432.89  467.24  468.96   465.9   478.8  461.99  485.36  462.09
   495.2  465.85  498.48  466.31  508.32  465.43  521.43  462.36  541.11  462.47
  555.43  461.75  564.07  460.99  573.89   461.8  578.89  461.46  596.83   462.2
  616.49   465.4  659.08  466.07  672.18   467.1   711.5  468.31  793.41   475.4
  855.66  478.92  927.74  484.28   947.4  486.49 1032.58  490.61 1078.45  493.86
#Mann= 3 , 0 , 0
       0     .12       0  555.43    .045       0  578.89     .12       0
Bank Sta=555.43,578.89
XS Rating Curve= 0 ,0
Exp/Cntr=0.3,0.1

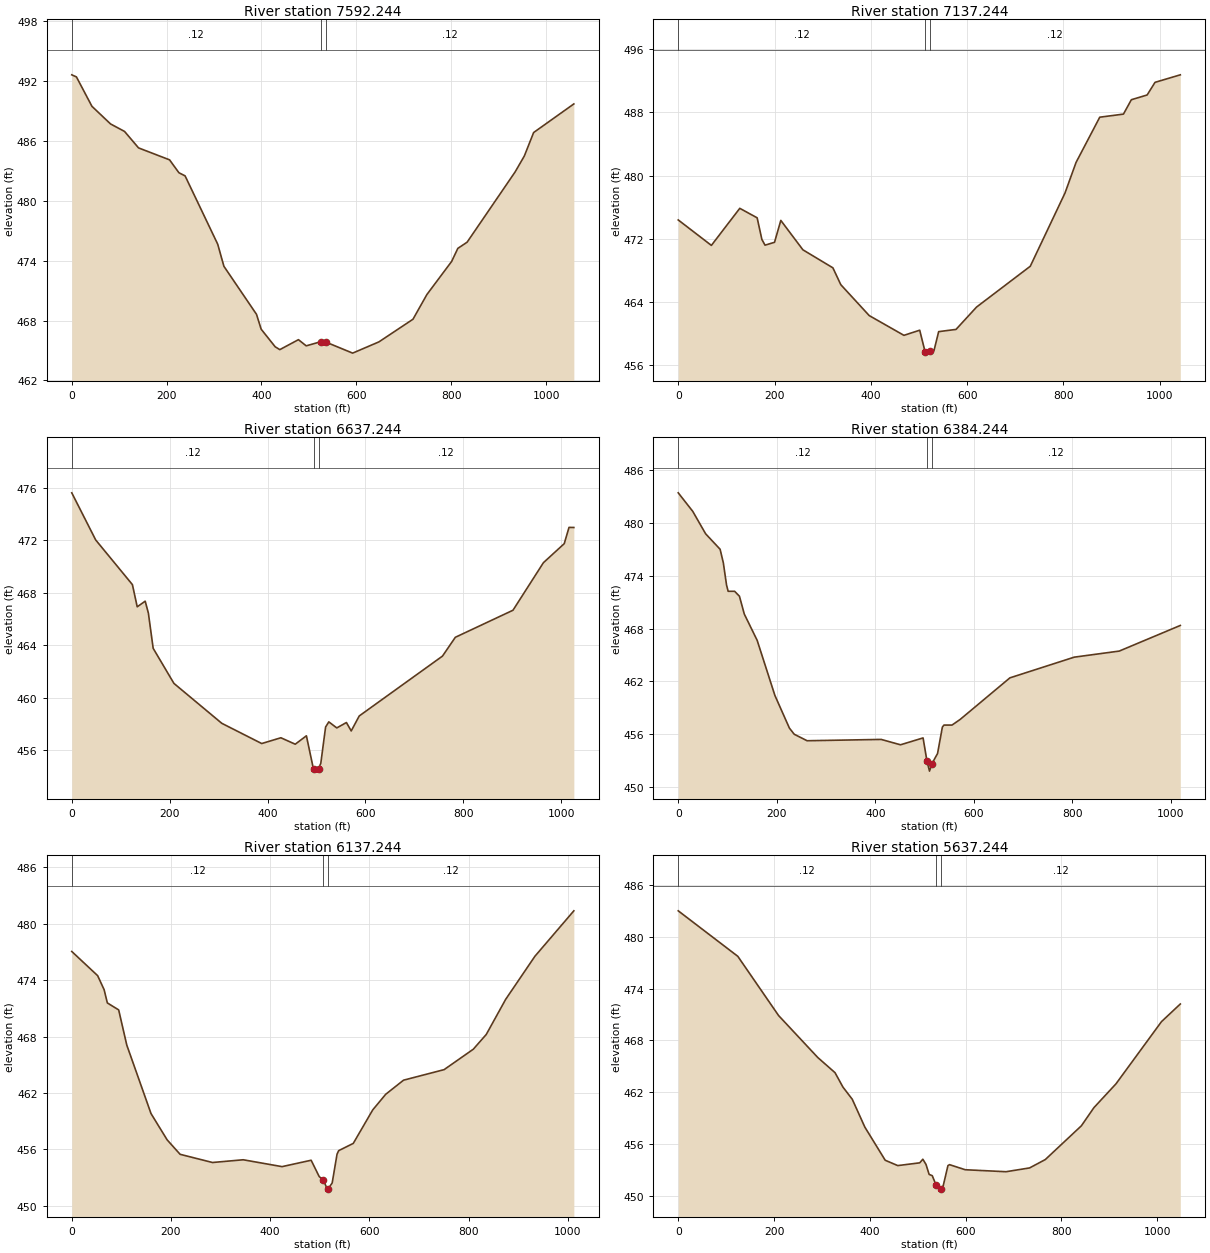
Type RM Length L Ch R = 1 ,7592.244,474.56,455,428.35
Node Name=1076
XS GIS Cut Line= 3
2425407.87548144276245.9877861892425201.50450312275757.489419356
2424995.91075419275270.830615774
#Sta/Elev= 30
       0  492.65    9.82  492.44   42.55  489.49   81.84  487.72   111.3  486.97
  140.76  485.32  206.23  484.12  225.87  482.83  238.96  482.51  307.71  475.66
   320.8  473.44  389.54  468.62  399.36  467.13  428.82  465.37  438.64  465.08
  477.93  466.08  494.29  465.46  524.71  465.87  535.65  465.84  592.26  464.73
   647.7  465.86  719.45  468.13   748.8  470.61  800.98  473.93  814.02  475.24
  833.59  475.86  934.68   482.9  954.25  484.51  973.82  486.86 1058.61  489.73
#Mann= 3 , 0 , 0
       0     .12       0  524.71    .045       0  535.65     .12       0
Bank Sta=524.71,535.65
XS Rating Curve= 0 ,0
Exp/Cntr=0.3,0.1

Type RM Length L Ch R = 1 ,7137.244,461.12,500,507.24
Node Name=1077
XS GIS Cut Line= 3
2425948.47216928275747.1065661012425502.51833677275483.563458025
2425050.60880752275216.501000017
#Sta/Elev= 30
       0  474.39   68.85  471.17  127.86  475.86  163.93  474.66  173.76  471.92
  180.32   471.2  199.99  471.56   213.1  474.33     259  470.61  321.29  468.33
  337.69   466.2   396.7  462.29  468.83  459.79  501.61  460.44   512.9  457.68
  514.73  457.54  523.15  457.81  531.13  457.82  540.97  460.26  577.06  460.54
  619.71  463.37  731.26  468.53  803.43   477.8   826.4  481.67  875.61  487.39
  924.82  487.78  941.22   489.6  974.03   490.2  990.44   491.8 1042.93  492.75
#Mann= 3 , 0 , 0
       0     .12       0   512.9    .045       0  523.15     .12       0
Bank Sta=512.9,523.15
XS Rating Curve= 0 ,0
Exp/Cntr=0.3,0.1

Type RM Length L Ch R = 1 ,6637.244,257.29,253,238.21
Node Name=1078
XS GIS Cut Line= 3
2426116.58535011 275575.088537442425813.64763577275178.716298684
2425493.79591328274760.213198692
#Sta/Elev= 30
       0  475.61   48.91  472.02   123.9  468.62  133.69  466.93  149.99  467.36
  156.51  466.45  166.29  463.77  208.68   461.1   306.5  458.06  388.02  456.52
  427.15  456.96  456.49  456.47  479.32  457.11  493.86  454.55  495.62  454.42
  504.03  454.61   508.7  455.01  518.51  457.78  525.05  458.17  541.41  457.71
  561.04  458.12  570.86  457.48  587.22  458.62  757.34  463.18  783.52  464.61
   901.3  466.67  963.46  470.29 1005.99  471.74  1015.8  472.98 1025.62  472.97
#Mann= 3 , 0 , 0
       0     .12       0  493.86    .045       0  504.03     .12       0
Bank Sta=493.86,504.03
XS Rating Curve= 0 ,0
Exp/Cntr=0.3,0.1

Type RM Length L Ch R = 1 ,6384.244,239.03,247,251.11
Node Name=1079
XS GIS Cut Line= 3
2426380.28396969275323.6057726892425972.60597928275017.292080849
2425565.71965395274711.572876021
#Sta/Elev= 30
       0  483.42   29.42  481.32   55.57  478.77   84.99  477.01   91.53  475.47
   98.06  472.94  101.33  472.24  114.41  472.24  124.21  471.68  134.02  469.66
  160.17  466.67  196.13  460.42  225.55  456.71  235.35  456.01   261.5  455.27
  411.87  455.42  451.09  454.81  496.86  455.59  504.69  452.99  509.93  451.82
  514.87  452.67  526.24  453.82  536.03  456.82  539.29  457.05   555.6  457.05
  571.92  457.68  673.05  462.41  803.55  464.76   894.9  465.45 1018.87  468.36
#Mann= 3 , 0 , 0
       0     .12       0  504.69    .045       0  514.87     .12       0
Bank Sta=504.69,514.87
XS Rating Curve= 0 ,0
Exp/Cntr=0.3,0.1

Type RM Length L Ch R = 1 ,6137.244,512.7,500,459.91
Node Name=1080
XS GIS Cut Line= 3
2426467.04232636275225.8661387712426130.08597927274840.475833431
2425800.80973494274463.869631276
#Sta/Elev= 30
       0  477.04   52.17  474.47   65.21  472.98   71.73  471.57   94.56  470.83
  110.86   467.1  159.77  459.81  192.38  457.01  218.46  455.48  283.68  454.61
  345.63   454.9  423.89  454.17  482.58  454.85  498.88  453.11  506.71  452.79
  515.19  451.78  516.92  451.81     525  452.44  534.81   455.5  538.08  455.87
  567.51  456.64  606.74   460.2   632.9  461.86  668.87  463.36  750.61  464.48
  809.46  466.65  835.62  468.22  874.85  471.96  933.71  476.53 1012.18  481.36
#Mann= 3 , 0 , 0
       0     .12       0  506.71    .045       0  516.92     .12       0
Bank Sta=506.71,516.92
XS Rating Curve= 0 ,0
Exp/Cntr=0.3,0.1

Type RM Length L Ch R = 1 ,5637.244,479.83,500,501.33
Node Name=1081
XS GIS Cut Line= 3
2426810.83264928274697.969556764 2426318.5518097274467.602235347
2425861.28697619274253.621036023
#Sta/Elev= 30
       0  483.04  124.42  477.76  209.55  470.89   291.4  466.02  327.42  464.26
  343.79   462.6  363.44  461.17  389.63  457.95  432.19   454.1  458.39  453.48
  504.23   453.8  510.77  454.22  517.32  453.62  523.87  452.46  530.42  452.31
  538.42  451.22  546.79  450.75  548.21  450.82  553.35  451.15  563.19  453.48
  566.46  453.59  599.25     453  684.48  452.77  733.66  453.21  766.44  454.18
  841.84   458.1  868.07  460.21  913.96  462.96 1009.03  470.18 1048.37  472.23
#Mann= 3 , 0 , 0
       0     .12       0  538.42    .045       0  548.21     .12       0
Bank Sta=538.42,548.21
XS Rating Curve= 0 ,0
Exp/Cntr=0.3,0.1

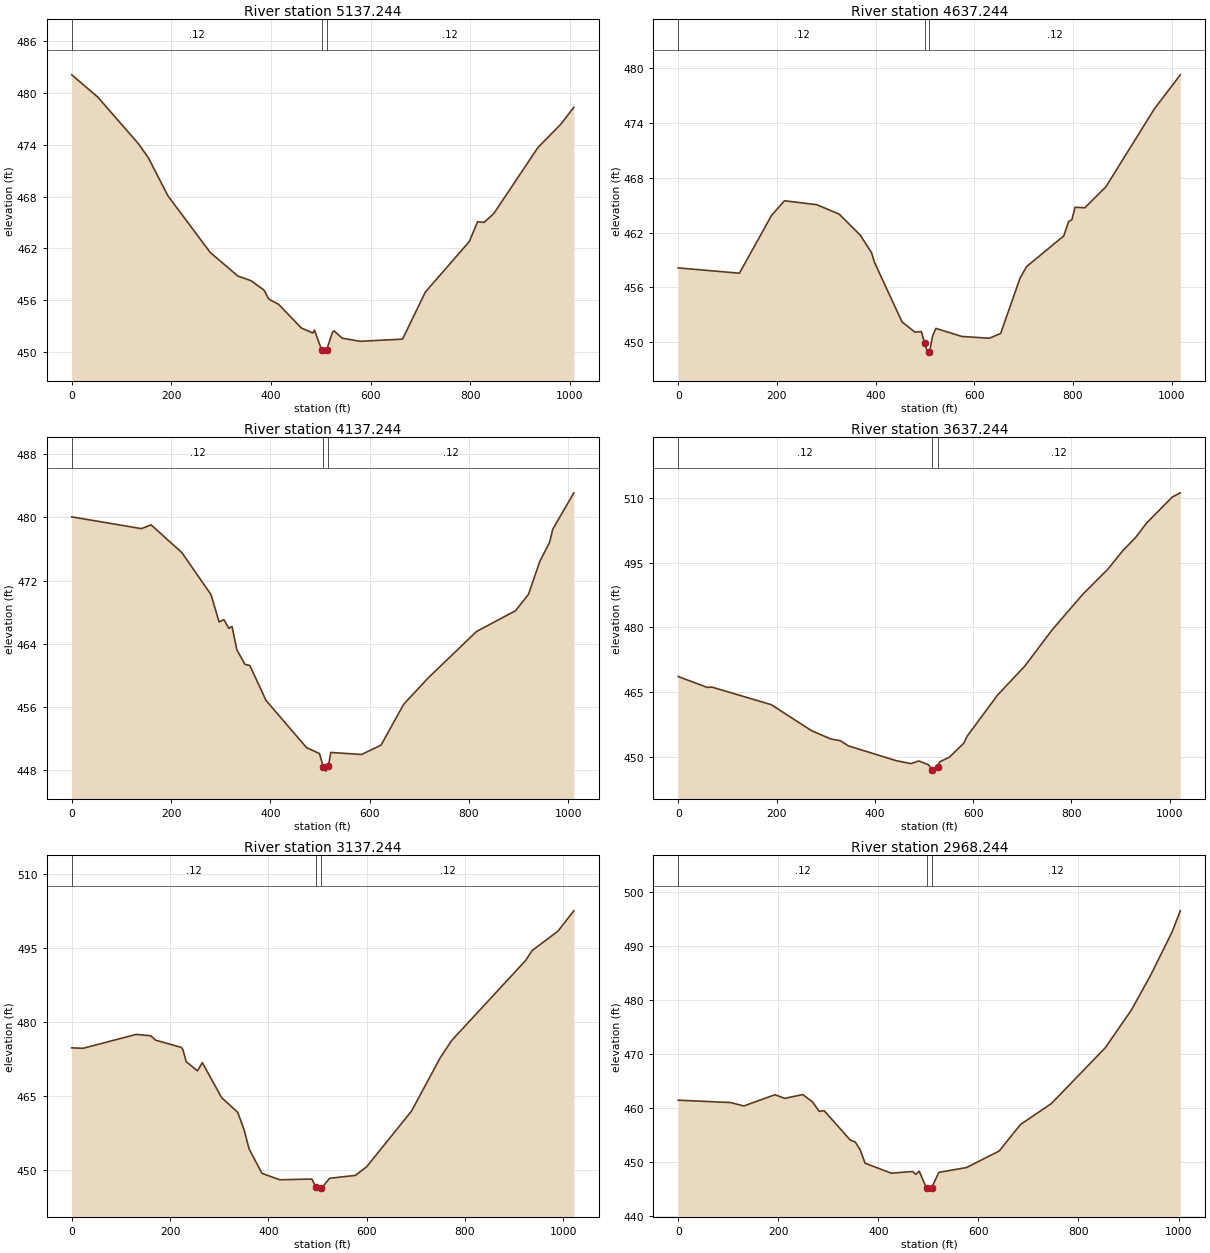
Type RM Length L Ch R = 1 ,5137.244,483.76,500,487.56
Node Name=1082
XS GIS Cut Line= 3
 2426900.0742687274376.8130468582426503.01043028274061.781524688
2426110.44363011273750.317908764
#Sta/Elev= 30
       0   482.1   52.32  479.52  134.07  474.11  153.69  472.51  192.93  468.11
  277.95  461.54  333.55  458.81  359.71  458.28  385.87  457.19  395.68  456.14
   415.3  455.54  461.08  452.79  483.97  452.22  487.24  452.56  501.84  450.22
  506.86  449.89  511.86   450.3  523.23  452.29  526.51  452.47  542.89  451.62
  578.91  451.26  664.07  451.51  709.92  456.96  798.36  462.83  814.73   465.1
  827.83  465.02  847.49  466.06  935.92  473.69  981.77  476.38 1007.97  478.35
#Mann= 3 , 0 , 0
       0     .12       0  501.84    .045       0  511.86     .12       0
Bank Sta=501.84,511.86
XS Rating Curve= 0 ,0
Exp/Cntr=0.3,0.1

Type RM Length L Ch R = 1 ,4637.244,495.28,500,497.37
Node Name=1083
XS GIS Cut Line= 3
2427222.58805937273924.9458403592426766.06141336 273707.13984552
2426304.19586727273486.786611691
#Sta/Elev= 30
       0  458.12  124.01  457.54  189.28  463.89  215.38  465.48  280.65  465.05
  326.34  464.01  368.76  461.72   391.6  459.81  398.13  458.68  453.61   452.2
  479.72  451.08  492.77  451.14  499.25   449.9  505.82  448.78  509.23   448.9
  515.66   450.7  522.22  451.49  574.71  450.61  630.48  450.41  653.44  450.94
   692.8     457  705.92  458.26  781.37  461.63  791.21   463.2  797.78   463.4
  804.34  464.77  824.02  464.71  866.66     467  965.07  475.56 1017.56  479.28
#Mann= 3 , 0 , 0
       0     .12       0  499.25    .045       0  509.23     .12       0
Bank Sta=499.25,509.23
XS Rating Curve= 0 ,0
Exp/Cntr=0.3,0.1

Type RM Length L Ch R = 1 ,4137.244,459.49,500,472.35
Node Name=1084
XS GIS Cut Line= 3
2427408.61393403273510.8679283562426956.09613827273271.454365194
2426514.74531494273037.949254766
#Sta/Elev= 30
       0  480.05  140.22  478.56  159.78  479.04  221.74  475.53  280.43  470.22
  296.73  466.76  306.52  467.05   316.3  465.95  322.82  466.19   332.6  463.22
  348.91  461.39  358.69  461.25   391.3  456.83  472.82  450.87  498.91  450.11
  506.97  448.37  511.95  447.89  517.03   448.6  521.74  450.25  583.75     450
  622.91  451.18   668.6  456.35  717.55  459.66  815.45  465.56  893.78  468.18
  919.89  470.25  942.73  474.43  962.31  476.81  968.84  478.49 1011.26  483.09
#Mann= 3 , 0 , 0
       0     .12       0  506.97    .045       0  517.03     .12       0
Bank Sta=506.97,517.03
XS Rating Curve= 0 ,0
Exp/Cntr=0.3,0.1

Type RM Length L Ch R = 1 ,3637.244,482.86,500,441.25
Node Name=1085
XS GIS Cut Line= 3
2427631.00128452273238.4803497642427204.13993353272937.522946432
2426796.09744252272649.833889276
#Sta/Elev= 30
       0  468.66   58.76  466.16   68.55  466.22  189.33  462.16  270.94  456.18
  310.11  454.25   329.7  453.84  346.02  452.65  443.95  449.21  473.32  448.55
  489.65  449.16  509.23  448.27  516.75  447.14  519.03  446.81  522.29  446.88
  527.59  447.83  532.08  448.97  551.66  450.03  581.03  453.26  587.55  454.83
  649.55  464.36  705.03  471.06   760.5  479.41   822.5  487.59  874.71  493.54
  904.08  497.68  930.18  500.73  953.02  504.13 1005.23  510.13 1021.55   511.1
#Mann= 3 , 0 , 0
       0     .12       0  516.75    .045       0  527.59     .12       0
Bank Sta=516.75,527.59
XS Rating Curve= 0 ,0
Exp/Cntr=0.3,0.1

Type RM Length L Ch R = 1 ,3137.244,159.08,169,165.15
Node Name=1086
XS GIS Cut Line= 3
 2427902.2651777272591.9160261012427400.57589236272590.277249858
2426880.73244385272588.579090521
#Sta/Elev= 30
       0   474.7   22.95  474.61  131.16  477.43  160.67  477.15  170.51  476.26
  222.97  474.79  226.25  474.32  232.81  471.91  255.76  470.04   265.6   471.7
  304.95  464.61  337.74  461.62  350.86  458.03  360.69  454.25  386.93  449.26
  422.99  447.96  488.58   448.1  496.42  446.52  504.96  446.06  507.81  446.22
  524.58  448.26  576.89  448.84  599.78  450.57  691.32  461.89  750.17  472.78
  773.06   476.2  923.45  492.42  936.53  494.42  988.84  498.33 1021.54  502.48
#Mann= 3 , 0 , 0
       0     .12       0  496.42    .045       0  507.81     .12       0
Bank Sta=496.42,507.81
XS Rating Curve= 0 ,0
Exp/Cntr=0.3,0.1

Type RM Length L Ch R = 1 ,2968.244,332.45,331,327.34
Node Name=1087
XS GIS Cut Line= 3
2427903.05290577272483.2653247712427404.11164644272435.036090523
 2426904.2100872272386.714336768
#Sta/Elev= 30
       0  461.45  104.84  461.01  131.05  460.38   193.3  462.46  212.96  461.79
     249  462.49  268.65   461.1  281.76  459.38  291.59  459.51  344.01  454.06
  353.84  453.72  363.66  452.26  373.49  449.79  425.91  447.95  468.51  448.26
  475.06  447.73  481.61  448.33   496.3  445.17  501.27     445  506.27  445.21
  520.84   448.1  576.28  448.99   641.5  452.05   683.9  456.94  745.86  460.83
  853.48  471.14  905.66  478.12   944.8  484.67  987.19  492.59  1003.5  496.47
#Mann= 3 , 0 , 0
       0     .12       0   496.3    .045       0  506.27     .12       0
Bank Sta=496.3,506.27
XS Rating Curve= 0 ,0
Exp/Cntr=0.3,0.1

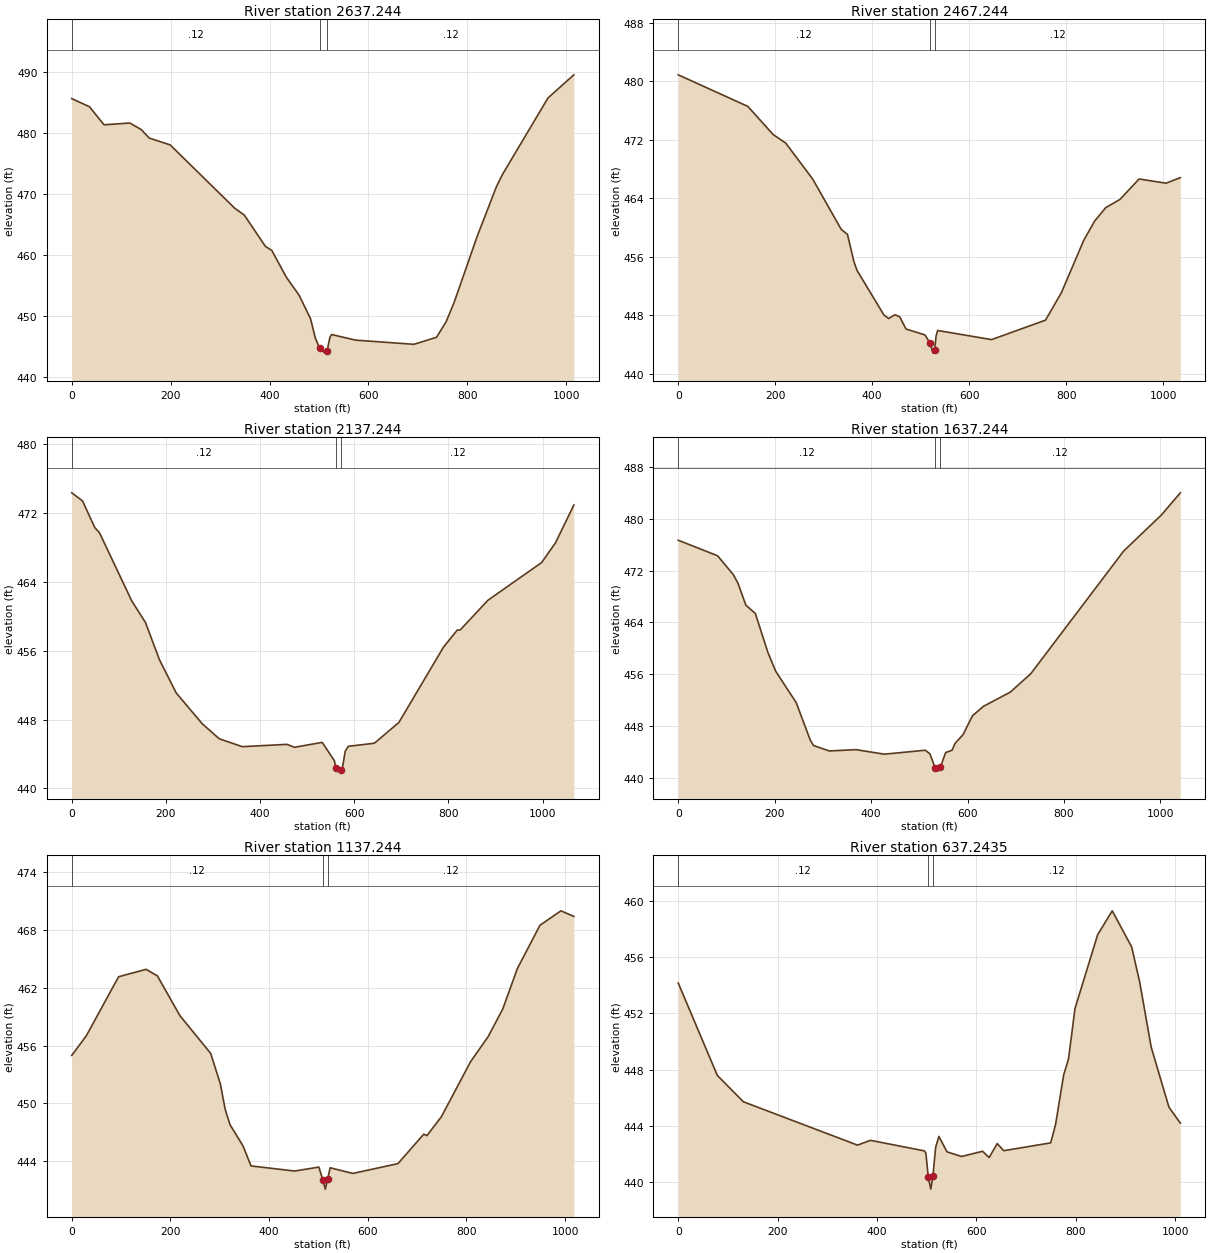
Type RM Length L Ch R = 1 ,2637.244,160.52,170,172.66
Node Name=1088
XS GIS Cut Line= 3
2427951.77590545272143.9149536042427443.76543853272111.529519692
2426938.34420528272079.309439763
#Sta/Elev= 30
       0   485.7   35.89  484.36   65.26   481.4  117.47  481.69  140.31  480.62
  156.63  479.22  199.05  478.09  329.57  467.69  349.15  466.54  391.57  461.42
  404.62  460.75  433.99  456.35   460.1  453.35  482.94  449.52  492.73  446.33
  501.31  444.67  512.31  443.87  516.22  444.18  522.11  446.45  525.38  446.93
  574.39     446  692.02  445.32  737.76  446.47  757.37  449.06   773.7  452.28
  819.45  462.94  858.66  471.18  871.73  473.32  963.21  485.81 1015.49  489.61
#Mann= 3 , 0 , 0
       0     .12       0  501.31    .045       0  516.22     .12       0
Bank Sta=501.31,516.22
XS Rating Curve= 0 ,0
Exp/Cntr=0.3,0.1

Type RM Length L Ch R = 1 ,2467.244,304.97,330,243.62
Node Name=1089
XS GIS Cut Line= 3
2427959.07313494272066.3576940152427445.81366278271954.644990936
2426947.17620862271846.114368096
#Sta/Elev= 30
       0  480.89  143.55  476.57  195.76  472.72  221.86  471.54  277.32  466.63
  336.05  459.76   349.1  459.05  362.15  455.38  368.67  454.14  424.14  448.04
  433.92  447.55  446.97  448.06  456.76  447.79  469.81  446.11  508.96   445.3
  519.16   444.2  525.28  442.81  528.73  443.22  531.82  445.14  535.09  445.91
  646.31  444.66  757.53  447.32  790.25  451.07  836.04  458.19  858.94  460.89
  881.84  462.72  911.28  463.85  950.54  466.64 1006.15  466.06 1035.59  466.82
#Mann= 3 , 0 , 0
       0     .12       0  519.16    .045       0  528.73     .12       0
Bank Sta=519.16,528.73
XS Rating Curve= 0 ,0
Exp/Cntr=0.3,0.1

Type RM Length L Ch R = 1 ,2137.244,443.77,500,450.37
Node Name=1090
XS GIS Cut Line= 3
2427990.74269103271745.8724426032427422.95576885271752.124070525
2426924.28386594271757.614545107
#Sta/Elev= 30
       0  474.34   22.84   473.4   48.95   470.3   58.74  469.72  127.27   461.8
  156.64  459.27  186.01  454.98  221.91  451.09  277.38   447.5  313.28  445.77
  362.23  444.85  456.87  445.12  473.18  444.78  531.92  445.35  558.03  443.21
  560.56  442.38  567.82  442.01  572.53   442.1  574.34  442.18  580.86  444.32
  587.38  444.89  642.79  445.25  694.94  447.67  789.47   456.4   818.8  458.39
  825.32  458.42  883.99  461.86  998.08  466.24 1027.41  468.52 1066.52  472.92
#Mann= 3 , 0 , 0
       0     .12       0  560.56    .045       0  572.53     .12       0
Bank Sta=560.56,572.53
XS Rating Curve= 0 ,0
Exp/Cntr=0.3,0.1

Type RM Length L Ch R = 1 ,1637.244,447.83,500,478.38
Node Name=1091
XS GIS Cut Line= 3
2428029.54445069271537.3508780152427511.10716736271392.341981694
2427026.79350345271256.877685681
#Sta/Elev= 30
       0  476.71   81.57  474.31  114.19   471.4  123.98  470.05  140.29  466.67
  159.87  465.39  185.97  459.36  202.28  456.44   244.7   451.6  274.06  445.76
  280.59  444.97  313.21  444.13  368.68  444.33   427.4  443.63  512.23  444.24
  522.02  443.68  532.69  441.53  538.33  441.01  543.53   441.6  554.66  443.89
  567.72  444.23  574.26  445.32  590.58  446.64  610.18  449.57  633.04  451.03
  688.55  453.22     731  456.06  923.67  475.03 1002.05  480.62 1041.24  484.04
#Mann= 3 , 0 , 0
       0     .12       0  532.69    .045       0  543.53     .12       0
Bank Sta=532.69,543.53
XS Rating Curve= 0 ,0
Exp/Cntr=0.3,0.1

Type RM Length L Ch R = 1 ,1137.244,489.05,500,501.99
Node Name=1092
XS GIS Cut Line= 3
2428112.32414077 271099.464286612427603.27988328271028.453601852
2427104.36749527270958.855972022
#Sta/Elev= 30
       0  454.98   29.46  457.01   94.94  463.15  150.59  463.92  173.51  463.24
  219.34   459.1  281.54  455.19  301.18  452.02     311  449.36  320.82  447.77
  347.01  445.58  363.38  443.49  451.77  442.96  500.88  443.37  508.93  442.03
  513.97  441.08   518.9  442.17  523.79   443.3  569.58  442.71  661.17  443.73
  713.51  446.79  720.05  446.64  749.49  448.63  808.37  454.32  844.35  456.95
  873.79  459.82  903.23     464  949.03   468.5  991.55     470 1017.72  469.42
#Mann= 3 , 0 , 0
       0     .12       0  508.93    .045       0   518.9     .12       0
Bank Sta=508.93,518.9
XS Rating Curve= 0 ,0
Exp/Cntr=0.3,0.1

Type RM Length L Ch R = 1 ,637.2435,648.15,635.24,610.71
Node Name=1093
XS GIS Cut Line= 3
2428178.42538652270746.3590216932427700.86531803270572.731416181
2427229.02538244 270401.18385902
#Sta/Elev= 30
       0  454.17   78.68  447.58  131.13   445.7  360.62  442.61  386.85  442.95
  495.03   442.2  498.31  442.04  503.12  440.31  508.14  439.47  512.42  440.39
  517.92  442.45  524.44  443.23  540.75  442.13  570.09   441.8  612.47  442.17
  625.51  441.72  641.81  442.72  654.85  442.21  749.39  442.77  759.17  444.07
  775.47  447.61  785.25  448.75  798.29  452.35  843.93  457.62  873.28  459.32
   912.4  456.74   928.7   454.2  951.52  449.61  987.38  445.31  1010.2  444.18
#Mann= 3 , 0 , 0
       0     .12       0  503.12    .045       0  512.42     .12       0
Bank Sta=503.12,512.42
XS Rating Curve= 0 ,0
Exp/Cntr=0.3,0.1