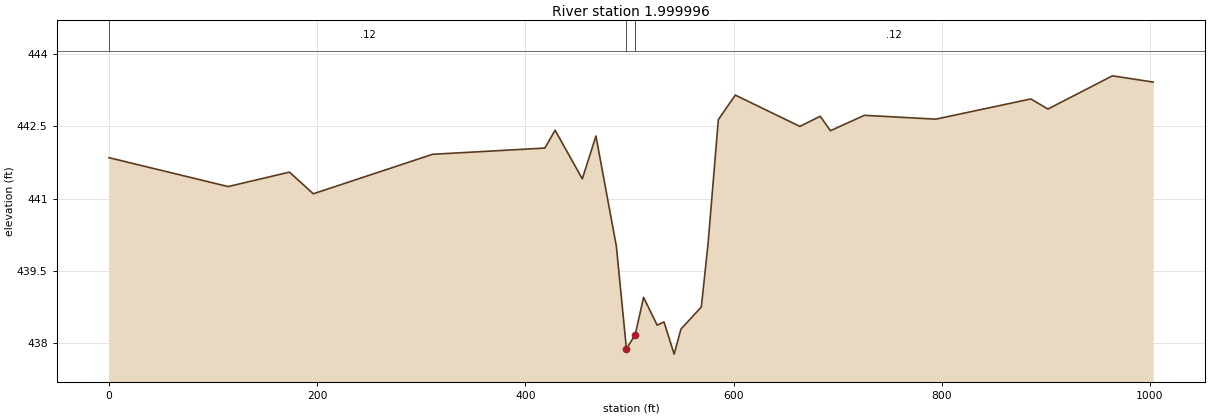
HEC-RAS study NorthForkBullskinRu.prj: NorthForkBullskinRun

--- NorthForkBullskinRu.g01 (geometry) --- (continued)

Type RM Length L Ch R = 1 ,1.999996,3.62,2,12.2
Node Name=1094
XS GIS Cut Line= 3
2428109.98195386269863.8571777642427628.02327211269998.959925935
2427144.01472569270134.637148023
#Sta/Elev= 30
       0  441.85   114.5  441.25  173.39  441.55  196.29   441.1  310.79  441.92
  418.75  442.05  428.56  442.42  454.74  441.41  467.82   442.3  487.45  440.01
   497.1  437.88  505.49  438.17  513.59  438.95  526.65  438.37  533.18  438.44
  542.97  437.77   549.5  438.29  569.08  438.75  575.61  440.08   585.4  442.64
  601.72  443.15  663.74   442.5  683.32  442.71  693.12  442.41  725.76  442.73
   794.3  442.65   885.7  443.07  902.02  442.86  964.03  443.55  1003.2  443.42
#Mann= 3 , 0 , 0
       0     .12       0   497.1    .045       0  505.49     .12       0
Bank Sta=497.1,505.49
XS Rating Curve= 0 ,0
Exp/Cntr=0.3,0.1

Chan Stop Cuts=-1
Use User Specified Reach Order=0
Composite Channel Slope=5